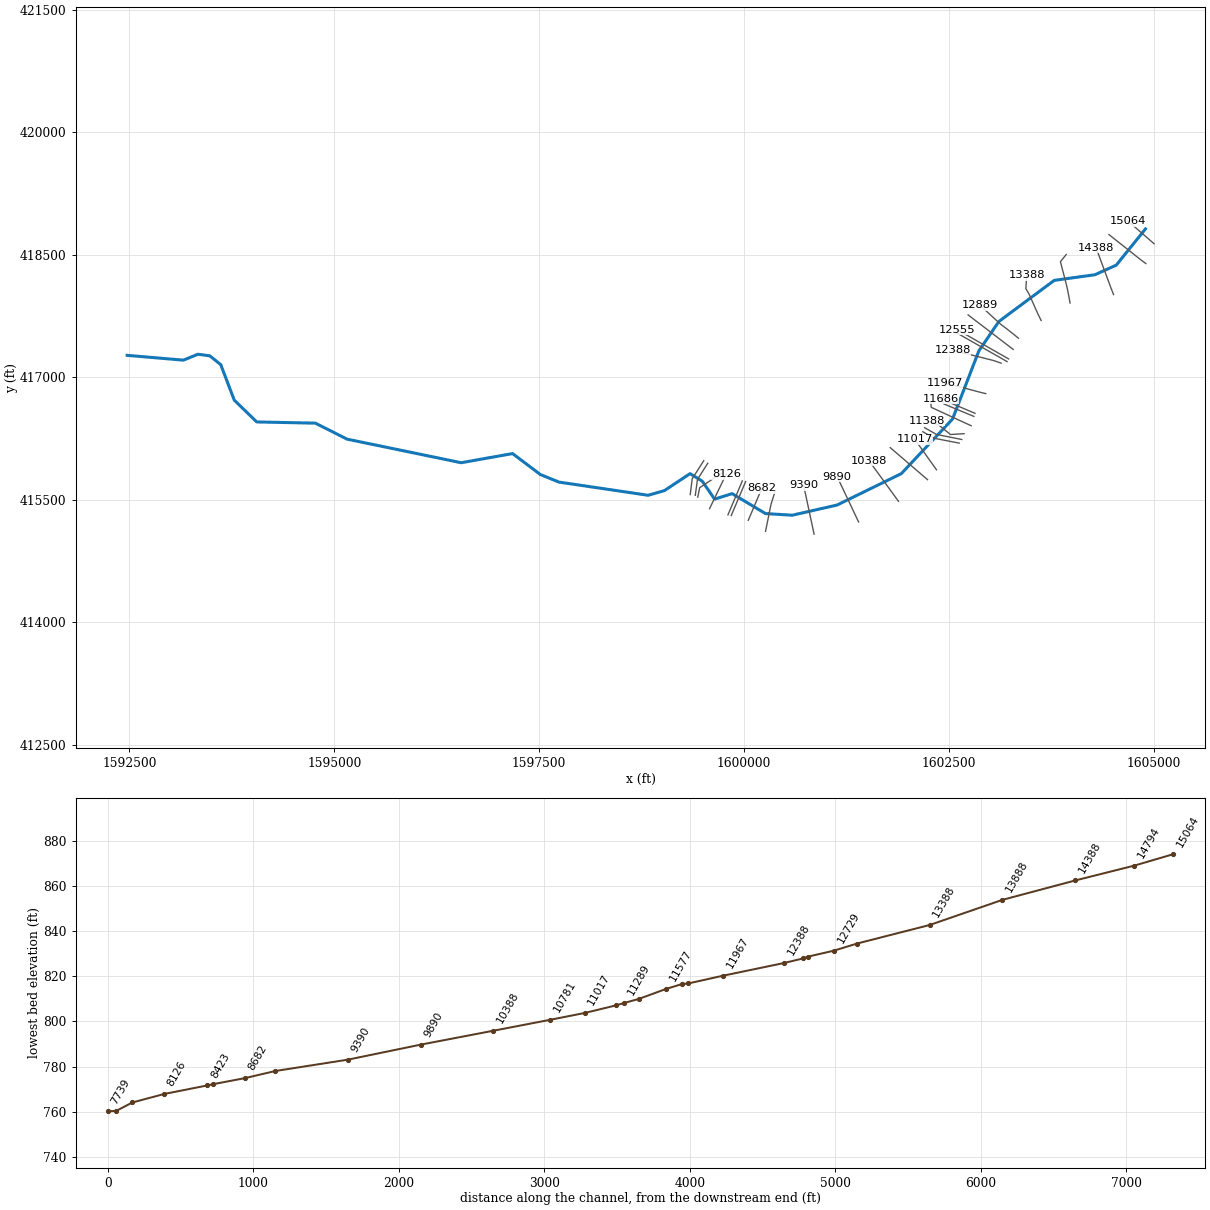
--- DOOLINRN.prj (project) ---

Proj Title=DOOLINRN
Current Plan=p01
Default Exp/Contr=0,0
English Units
Geom File=g01
Flow File=f01
Plan File=p01
BEGIN DESCRIPTION:
---------- MODELED AS PART OF WVEMD CTP PROGRAM, 2023----------
Stream Name: Doolin Run
Flood Zone:  AFH
Wetzel County, WV
HEC-RAS Version: RAS 6.3
Vertical Datum: NAVD88
Projection: NAD 1983 StatePlane West Virginia S FIPS 4702 (US Feet)
Terrain: 1-meter West Virginia FEMA R3 South Central (collected 2018-2020)
Land Use: 2019 NLCD
Hydrologic Method:
WV 2010 Regional Regression Equations
Additional Model Notes:
WSEL tie in with effective
END DESCRIPTION:
DSS Export Rating Curves= 0
DSS Export Rating Curve Sorted= 0
DSS Export Volume Flow Curves= 0
DXF OffsetX= 0
DXF OffsetY= 0
DXF ScaleX= 0
DXF ScaleY= 0

--- DOOLINRN.p01 (plan) ---

Plan Title=Floodplain
Program Version=6.30
Short Identifier=Floodplain
Geom File=g01
Flow File=f01
Subcritical Flow
K Sum by GR= 0
Std Step Tol= 0.01
Critical Tol= 0.01
Num of Std Step Trials= 20
Max Error Tol= 0.3
Flow Tol Ratio= 0.001
Split Flow NTrial= 30
Split Flow Tol= 0.02
Split Flow Ratio= 0.02
Log Output Level= 0
Friction Slope Method= 1
Unsteady Friction Slope Method= 2
Unsteady Bridges Friction Slope Method= 1
Parabolic Critical Depth
Global Vel Dist= 0 , 0 , 0
Global Log Level= 0
CheckData=True
Encroach Param=-1 ,0,0, 0
Mapping Interval=1HOUR
Computation Time Step Use Courant=        0
Computation Time Step Use Time Series=    0
Computation Time Step Count To Double=0
Computation Time Step Max Doubling=0
Computation Time Step Max Halving=0
Computation Time Step Residence Courant=0
Run HTab= 0
Run UNet= 0
Run Sediment= 0
Run PostProcess= 0
Run WQNet= 0
Run RASMapper= 0
UNET Theta= 0
UNET Theta Warmup= 0
UNET ZTol= 0
UNET ZSATol= 0
UNET MxIter= 0
UNET Max Iter WO Improvement= 0
UNET MaxInSteps= 0
UNET DtIC= 0
UNET DtMin= 0
UNET MaxCRTS= 0
UNET WFStab= 0
UNET SFStab= 0
UNET WFX= 1
UNET SFX= 1
UNET Gravity=32.17405
UNET 1D Methodology=Finite Difference
UNET DSS MLevel= 1
UNET Pardiso=0
UNET DZMax Abort= 0
UNET Use Existing IB Tables= 0
UNET Froude Reduction=False
UNET Froude Limit= 0
UNET Froude Power= 0
UNET D1 Cores= 0
UNET WindReference=Eulerian
UNET WindDragFormulation=Hsu (1988)
UNET D2 Coriolis=0
UNET D2 Cores= 0
UNET D2 Theta= 1
UNET D2 Theta Warmup= 1
UNET D2 Z Tol= 0.01
UNET D2 Volume Tol= 0.01
UNET D2 Max Iterations= 20
UNET D2 Equation= 0
UNET D2 RampUpFraction=0.1
UNET D2 TimeSlices= 1
UNET D2 Turbulence Formulation=Non-Conservative (original)
UNET D2 Eddy Viscosity=0.3
UNET D2 Transverse Eddy Viscosity=0.1
UNET D2 Smagorinsky Mixing=0
UNET D2 BCVolumeCheck=0
UNET D2 Cores=0
UNET D2 SolverType=PARDISO (Direct)
UNET D2 Minimum Iterations= 3
UNET D2 Maximum Iterations= 30
UNET D2 Restart Number= 10
UNET D2 Relaxation Coeff=1.3
UNET D2 SOR Precondition Iterations= 10
UNET D2 ILUT Maximum Fill= 8
UNET D2 ILUT Tolerance=1E-08
UNET D2 Convergence Tolerance=0.00001
UNET D1D2 MaxIter= 0
UNET D1D2 ZTol=0.01
UNET D1D2 QTol=0.1
UNET D1D2 MinQTol=1
Write IC File= 0
Write IC File at Fixed DateTime=0
Write IC File at Sim End=0
Echo Input=False
Echo Parameters=False
Echo Output=False
Write Detailed= 0
HDF Write Warmup=0
HDF Write Time Slices=0
HDF Flush=0
HDF Compression= 1
HDF Chunk Size= 1
HDF Spatial Parts= 1
HDF Use Max Rows=0
HDF Fixed Rows= 1
Calibration Method= 0
Calibration Iterations= 20
Calibration Max Change=0.05
Calibration Tolerance=0.2
Calibration Maximum=1.5
Calibration Minimum=0.5
Calibration Optimization Method= 1
WQ AD Non Conservative
WQ ULTIMATE=-1
WQ Max Comp Step=1HOUR
WQ Output Interval=15MIN
WQ Output Selected Increments= 0
WQ Output face flow=0
WQ Output face velocity=0
WQ Output face area=0
WQ Output face dispersion=0
WQ Output cell volume=0
WQ Output cell surface area=0
WQ Output cell continuity=0
WQ Output cumulative cell continuity=0
WQ Output face conc=0
WQ Output face dconc_dx=0
WQ Output face courant=0
WQ Output face peclet=0
WQ Output face adv mass=0
WQ Output face disp mass=0
WQ Output cell mass=0
WQ Output cell source sink temp=0
WQ Output nsm pathways=0
WQ Output nsm derived pathways=0
WQ Create Restart=0
WQ Fixed Restart=0
WQ System Summary=0
WQ Write To DSS=0
Sorting and Armoring Iterations= 10
XS Update Threshold= 0.02
Bed Roughness Predictor= 0
Hydraulics Update Threshold= 0.02
Energy Slope Method= 1
Volume Change Method= 1
Sediment Retention Method= 0
Sediment TS Multiplier= 1
Warm Up Method= 0
XS Weighting Method= 0
Number of US Weighted Cross Sections= 1
Number of DS Weighted Cross Sections= 1
Upstream XS Weight=0
Main XS Weight=1
Downstream XS Weight=0
Number of DS XS's Weighted with US Boundary= 1
Upstream Boundary Weight= 1
Weight of XSs Associated with US Boundary= 0
Number of US XS's Weighted with DS Boundary= 1
Downstream Boundary Weight= 0.5
Weight of XSs Associated with DS Boundary= 0.5
Percentile Method= 0
Sediment Output Level= 3
Mass or Volume Output= 0
Output Increment Type= 1
Profile and TS Output Increment= 1
Transport Output Increment 1
XS Output Flag= 0
XS Output Increment= 10
Read HDF5 Sediment Hotstart= 0
Sediment Hotstart Type= 0
Write Gradation File= 0
Read Gradation Hotstart= 0
Write HDF5 File= 1
Write Binary Output= 1
Write DSS Sediment File= 0
DSS Sediment Output Type= 1
SV Curve= 0
Specific Gage Flag= 0
Subcell Erosion Methods= 0
Subcell Deposition Methods= 0
Advection Scheme= 1
Matrix Solver= 0
Implicit Weighting Factor= 1
Maximum Outer Loop Convergence Iterations= 5
Convergence Maximum Absolute= 0.001
Convergence RMSE= 0.0001
Grain Fractions Max Abs Error= 0.001
Max Subgrid Regions= 1
Max Subgrid Length Scale= 3.402823E+38
Initial Layer Thickness= 3.402823E+38
Min Layer Thickness= 3.402823E+38
Max Layer Thickness= 3.402823E+38
Number of Layers= 5

--- DOOLINRN.f01 (steady flow) ---

Flow Title=Flow
Program Version=6.30
Number of Profiles= 1
Profile Names=F01pct
River Rch & RM=River 1,Reach 1         ,15064
     690
River Rch & RM=River 1,Reach 1         ,11289
     988
River Rch & RM=River 1,Reach 1         ,7583
    1250
River Rch & RM=River 1,Reach 1         ,6713
    1440
River Rch & RM=River 1,Reach 1         ,0
    1620
Boundary for River Rch & Prof#=River 1,Reach 1         , 1
Up Type= 0
Dn Type= 1
Dn Known WS=678.8
DSS Import GetInterval= 0
DSS Import GetPeak= 0
DSS Import FillOption= 0

--- DOOLINRN.g01 (geometry) ---

Geom Title=Geometry
Program Version=6.30

River Reach=River 1         ,Reach 1
Reach XY= 30
1604899.67873773418814.7298804071604543.28782873418371.342689142
1604284.52062973418254.1080154781603786.42418498418184.860450566
1603110.95670389417681.904435471 1602866.7678878417321.695510224
1602544.82758681416487.0800534781601920.38460997415818.901927903
1601135.50297765415434.167789236 1600589.7606308415309.833392233
1600262.31541957415329.7647828311599854.81431927 415573.72804603
1599640.83926225415506.3632792231599491.63224965415725.546799645
1599341.58224013415818.6721745431599028.46322848415610.703525394
1598830.09781156415553.7564608161597742.41002631415715.106531829
1597515.57091306415807.1706521511597175.78714381416064.381423831
1596548.42094448415952.3855848311595156.40787348416240.854177505
1594768.37182571416436.8155685661594053.19266723416451.621134892
1593778.89794022 416718.323029311593613.75161697417153.018354163
1593479.92609721417261.2179408971593334.71116456417280.200186402
 1593157.2262833417208.067128554 1592471.2522362417267.021633595

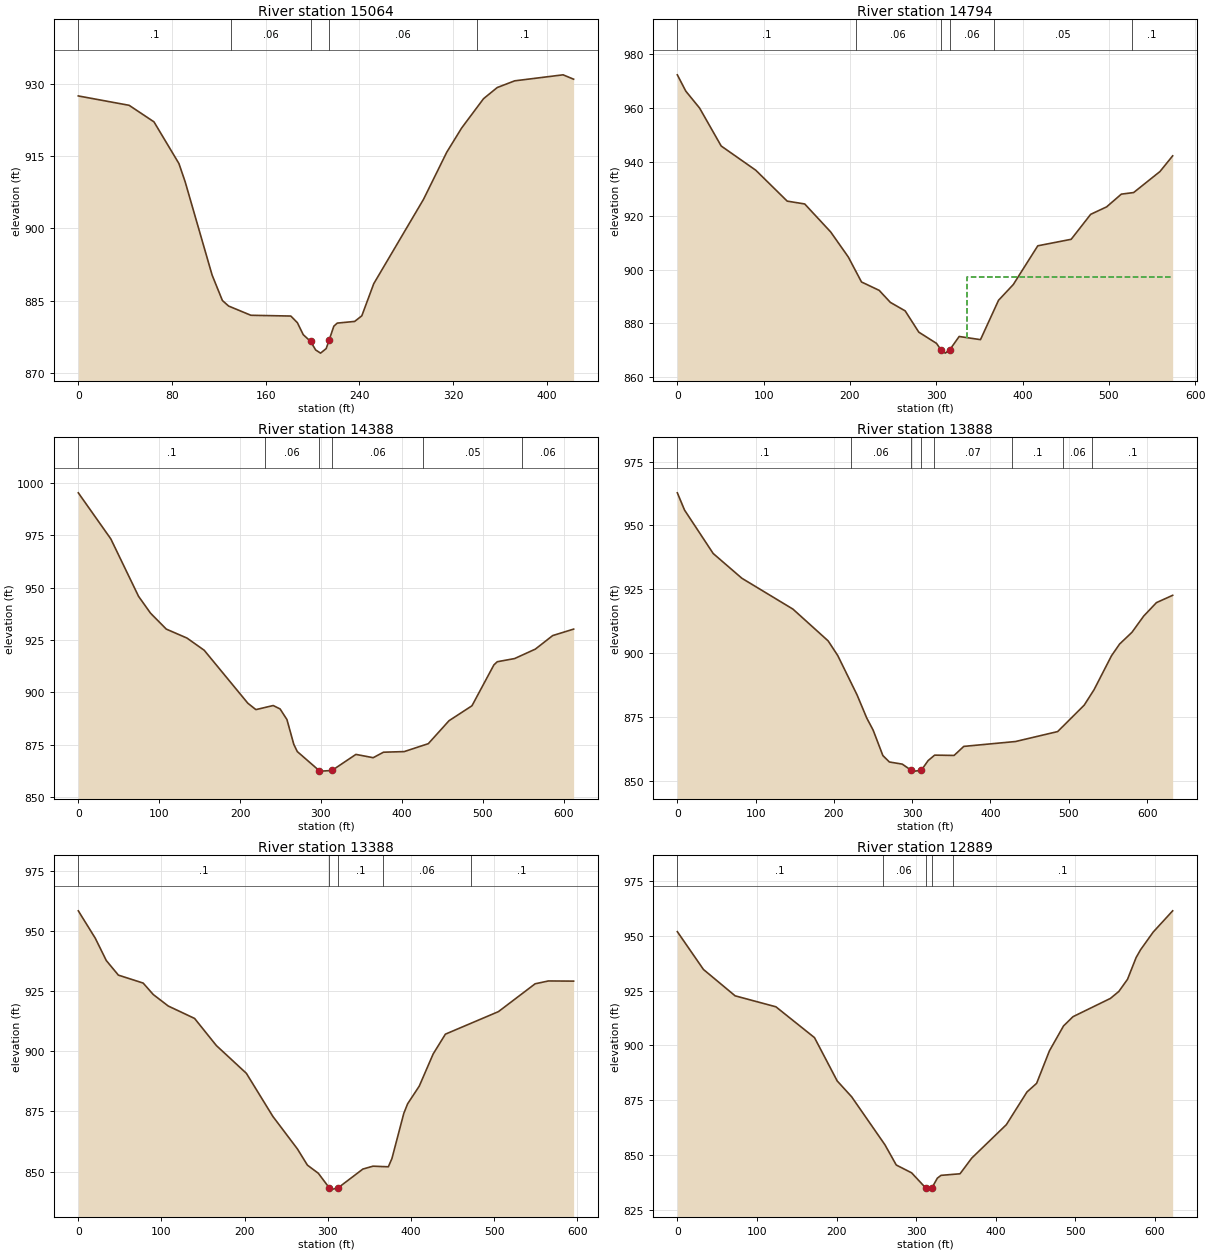
Type RM Length L Ch R = 1 ,15064   ,269.1,269.2,269
XS GIS Cut Line= 2
1605004.83103529418633.473608404 1604686.2003059418911.377101711
#Sta/Elev= 30
       0  927.53    43.4  925.58    64.6  922.14    85.9  913.47    91.2  909.69
   114.2   890.3     123     885   128.3  883.85   147.3  881.93   181.4  881.77
     187  880.39     192   877.9   198.3  876.49   202.6  874.72   206.8  874.06
   211.6  875.01  214.17876.8295   218.1  879.65     221   880.3   235.9  880.65
     242  881.82   252.2   888.5   294.7  906.05   314.5  915.83   327.2  920.86
   345.9  926.96   357.6  929.28   372.5  930.67   413.8  931.92   422.8  931.01
#Mann= 5 ,-1,0
       0      .1       0     130     .06       0   198.3    .045       0
  214.17     .06       0     340      .1       0
Bank Sta=198.3,214.17
XS Rating Curve= 0 ,0
Exp/Cntr(USF)=0,0
Exp/Cntr=0.3,0.1

Type RM Length L Ch R = 1 ,14794   ,410.2,406,401.8
XS GIS Cut Line= 3
1604904.73447992418390.6659018411604835.39073131 418442.67988346
1604453.74524005 418745.63216745
#Sta/Elev= 30
       0  972.42     9.8  966.36    25.8  960.06    50.8  945.97    90.9  936.96
   127.3  925.48   147.6  924.42   177.7  914.02   198.1  904.72   213.4  895.43
   233.9  892.31   246.9  887.83     264  884.69   279.8  876.78   300.3  872.61
   305.4  870.27   310.5  868.98  315.83870.2891   326.6  875.17   351.3  873.99
   372.2  888.61   389.3  894.47   417.7  908.87   456.4  911.29     479  920.57
   497.5  923.35   514.5  928.07   528.8  928.67   559.3  936.48     574  942.31
#Mann= 6 ,-1,0
       0      .1       0  206.68     .06       0   305.4    .045       0
  315.83     .06       0  366.68     .05       0  526.68      .1       0
#XS Ineff= 2 , 0
                          335.31          897.45
Permanent Ineff=
       F       F
Bank Sta=305.4,315.83
XS Rating Curve= 0 ,0
Exp/Cntr(USF)=0,0
Exp/Cntr=0.3,0.1

Type RM Length L Ch R = 1 ,14388   ,500.6,500,498.9
XS GIS Cut Line= 6
1604510.28723858418011.0835671721604476.24596809418098.450846508
1604445.93795784418180.5343437491604419.95900717418250.891158417
1604329.03464834418497.1409940121604295.69153917418584.766146839
#Sta/Elev= 30
       0   995.2    40.2  973.22    74.5  945.82    89.3  937.78   108.8  930.17
   134.4  925.89   155.7  920.07   209.6  894.82   219.6  891.75     241   893.7
   249.5  892.08     258     887   266.5  875.15   270.8  871.73  297.75862.6882
   300.7   862.4   313.6  862.71   343.3  870.38   364.6  868.81   377.4  871.43
     403  871.72   432.8   875.5   458.4  886.45   486.8  893.59   513.9  913.08
   518.1   914.6   539.5  916.11   565.2  920.63   586.6  927.08   612.5  930.17
#Mann= 6 ,-1,0
       0      .1       0  231.27     .06       0  297.75    .045       0
   313.6     .06       0  426.26     .05       0  548.76     .06       0
Bank Sta=297.75,313.6
XS Rating Curve= 0 ,0
Exp/Cntr(USF)=0,0
Exp/Cntr=0.3,0.1

Type RM Length L Ch R = 1 ,13888   ,497.3,500,499.9
XS GIS Cut Line= 6
1603979.45234226417907.4374490081603962.64069609418000.231554762
1603945.31822418418086.4118285921603928.10762867418159.434648424
1603861.60251234 418413.37049225 1603932.4827204418501.278276269
#Sta/Elev= 30
       0  962.74     9.2  955.99    45.8  938.99    82.4  929.31   147.7  917.22
   192.6   904.8   204.9  899.06   229.6  883.63   241.9  874.63   250.1  869.87
   262.5  859.93   270.8   857.4   287.3  856.56  298.54854.1965   303.9  853.82
  311.73 854.203   320.4  857.97   328.7  860.08   353.5  859.96   365.9   863.5
     432  865.41   485.8   869.3   519.7  879.64   532.3  885.69   554.6  898.99
   564.9  903.55   580.7  908.15   595.7  914.51     612  919.77   632.7  922.63
#Mann= 8 ,-1,0
       0      .1       0  222.21     .06       0  298.54    .045       0
  311.73     .06       0  327.23     .07       0  427.23      .1       0
  492.23     .06       0  529.73      .1       0
Bank Sta=298.54,311.73
XS Rating Curve= 0 ,0
Exp/Cntr(USF)=0,0
Exp/Cntr=0.3,0.1

Type RM Length L Ch R = 1 ,13388   ,497.6,499.6,501.7
XS GIS Cut Line= 6
1603626.10363951417694.173439845 1603585.2044431417778.588625342
1603549.48043318417858.4637936651603478.40675643 418018.38112475
1603439.84088868418083.3120972511603450.58257492418246.724909535
#Sta/Elev= 30
       0  958.29    20.4  946.92    33.7  937.62    48.2  931.58      78  928.28
    90.1  923.53   108.2  918.74   139.8   913.6     166  902.33   202.1  890.79
   233.9  872.92   263.5  859.37   275.5  852.65   288.6  849.28  301.61843.2949
   306.1  842.69   312.7   843.3   342.2  851.03   354.3  852.22   372.8  851.97
   377.1  855.38   391.4  874.17     396  878.14     410  885.49   426.7  898.83
   441.4  907.06   505.2  916.42   549.3  927.98   565.3  929.16   595.6  929.09
#Mann= 5 ,-1,0
       0      .1       0  301.61    .045       0   312.7      .1       0
   366.3     .06       0  471.82      .1       0
Bank Sta=301.61,312.7
XS Rating Curve= 0 ,0
Exp/Cntr(USF)=0,0
Exp/Cntr=0.3,0.1

Type RM Length L Ch R = 1 ,12889   ,158.8,159.3,158.9
XS GIS Cut Line= 6
1603350.17407326417476.4389671681603275.00755693   417537.438189
1603203.72587533417593.8740997611603141.24207643417640.678468093
1603066.89970542417707.8653415891602878.31707734417881.361057594
#Sta/Elev= 30
       0  951.91    32.8  934.67    72.6  922.64   123.8  917.64   172.3  903.57
   200.8  883.82   218.9  876.61   260.8  854.68     275  845.46   294.3  841.89
   311.8  835.08   315.8  834.46  319.82835.0664   326.6  839.45   331.2  840.74
   355.1  841.46   369.8  848.61   413.3  863.87   439.2  878.79   451.3  882.71
   467.4  897.55   485.1   908.9     497  913.13     544  921.46   554.6  924.64
   565.5  930.19   576.3  940.11   581.8  943.61   597.7  951.71   622.2  961.42
#Mann= 5 ,-1,0
       0      .1       0  257.72     .06       0   311.8    .045       0
  319.82     .06       0  345.79      .1       0
Bank Sta=311.8,319.82
XS Rating Curve= 0 ,0
Exp/Cntr(USF)=0,0
Exp/Cntr=0.3,0.1

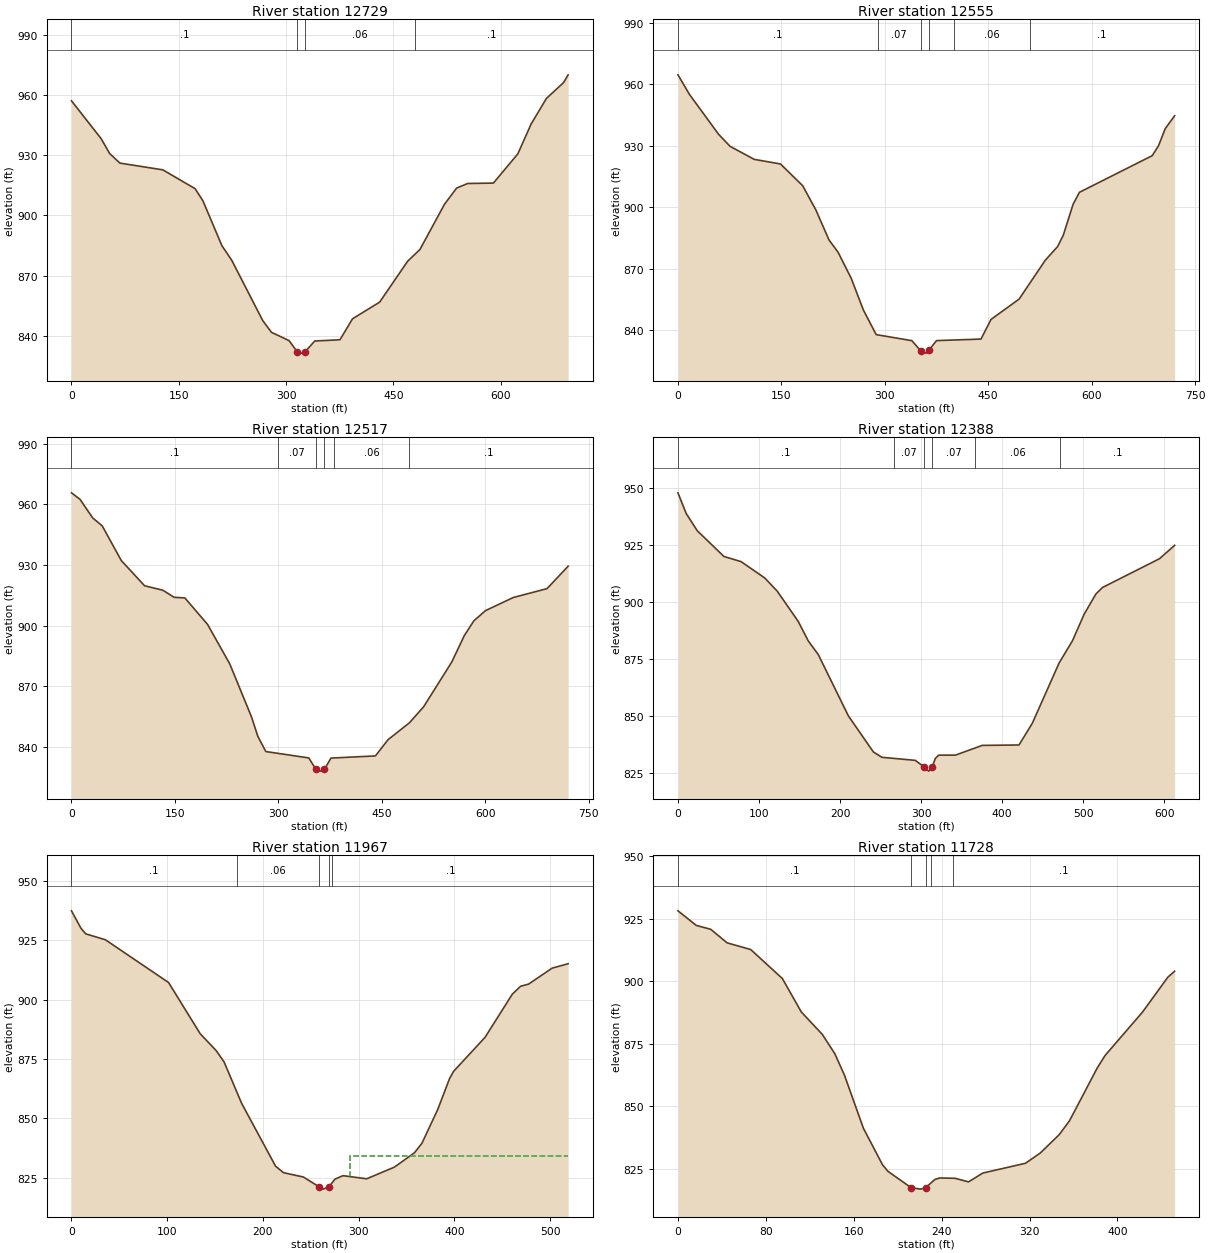
Type RM Length L Ch R = 1 ,12729   ,174,174.9,175.7
XS GIS Cut Line= 2
1603285.81631567417339.3121435971602735.02440553417762.075323161
#Sta/Elev= 30
       0  957.19    41.4  938.34    53.4  930.88    67.7  926.12   127.6  922.76
   172.8  913.36   183.7  907.32   210.3  884.89     224  877.65   267.4  847.51
   279.5  841.71   304.2  837.53   315.9  831.84   321.6  831.31  326.25  831.86
     340  837.35   375.3  837.97   392.9  848.45   430.8  856.76   469.9  877.15
   487.1  883.02   521.5  905.62   538.4  913.67   553.8  915.94   589.8  916.15
     624  930.75   642.5  945.58   663.9  958.37   687.9  966.28   694.3  970.16
#Mann= 4 ,-1,0
       0      .1       0   315.9    .045       0  326.25     .06       0
     480      .1       0
Bank Sta=315.9,326.25
XS Rating Curve= 0 ,0
Exp/Cntr(USF)=0,0
Exp/Cntr=0.3,0.1

Type RM Length L Ch R = 1 ,12555   ,37.8,37.8,37.9
XS GIS Cut Line= 2
1603229.73490014417223.3075288861602604.34974397417580.670475268
#Sta/Elev= 30
       0   964.7    16.7  955.12    58.9  935.66    75.6  929.76   110.6  923.39
   148.7  921.14   180.9  910.51     200  898.69     219  884.06   232.2  878.02
   251.3  865.25   268.9  849.79   287.5  837.75   339.2   834.8     352  829.87
   359.8  828.71  363.75830.0375     375  834.83   439.5  835.58     454  845.16
   494.8  855.13   532.7  874.08   550.7  880.82   558.8   886.3   573.1  901.47
   582.3   907.3   687.8   925.2   696.9     930   706.7   938.4   720.3  944.69
#Mann= 6 ,-1,0
       0      .1       0     290     .07       0     352    .045       0
  363.75     .07       0     400     .06       0     510      .1       0
Bank Sta=352,363.75
XS Rating Curve= 0 ,0
Exp/Cntr(USF)=0,0
Exp/Cntr=0.3,0.1

Type RM Length L Ch R = 1 ,12517   ,127,128.6,129.8
XS GIS Cut Line= 2
1603210.83589817417190.663798206  1602585.450742417548.026744589
#Sta/Elev= 30
       0  965.78    12.3  962.58    30.8  953.33    44.6  949.39    72.2  932.23
     106  919.72   132.4  917.52   148.9     914   164.4   913.7   197.3  900.59
   229.5  881.03   261.1   854.7   270.3  845.06   281.9  837.56   344.1   834.4
  354.41828.7969     361  827.86   366.9  828.79   376.3  834.33   440.8   835.4
   459.2  843.48     490  851.78   510.6   859.7   551.4  881.86   569.8  895.09
   583.6  902.37   600.4   907.4   640.7   913.9   689.6  918.29   720.3  929.42
#Mann= 6 ,-1,0
       0      .1       0     300     .07       0  354.41    .045       0
   366.9     .07       0     380     .06       0     490      .1       0
Bank Sta=354.41,366.9
XS Rating Curve= 0 ,0
Exp/Cntr(USF)=0,0
Exp/Cntr=0.3,0.1

Type RM Length L Ch R = 1 ,12388   ,421.5,421.4,421.5
XS GIS Cut Line= 6
1603137.74044301   417171.9152981603048.80820617417202.628819257
1602794.33693033417267.0529030111602721.63071093417285.459690332
1602636.80673359417306.9347130061602545.92404135417329.942869082
#Sta/Elev= 30
       0  947.95    10.2  938.85    23.8  931.33    56.7  920.04    77.9  917.77
   107.2  910.56   122.6  904.76   148.4  891.54   160.8  882.97   173.2  876.95
   210.3  850.08   241.1  834.28   251.6  831.93   292.9  830.58   303.8827.6507
   309.4  825.86   313.5  827.52   317.6  831.44   321.7  832.87   342.4  832.88
   375.4  837.15   420.8  837.33   437.3  846.91   470.3  873.31   486.8  883.07
   501.2  894.71   515.7  903.58   523.9  906.44   594.1  919.04   612.8  924.91
#Mann= 6 ,-1,0
       0      .1       0  266.59     .07       0   303.8    .045       0
   313.5     .07       0  366.59     .06       0  471.59      .1       0
Bank Sta=303.8,313.5
XS Rating Curve= 0 ,0
Exp/Cntr(USF)=0,0
Exp/Cntr=0.3,0.1

Type RM Length L Ch R = 1 ,11967   ,239.2,238.7,237.4
XS GIS Cut Line= 6
1602950.45475605416798.1766242531602865.49363988416819.177566498
1602696.53006704416864.7434202431602623.81991062416883.172845333
1602538.90111721416904.3397977491602447.87800529416926.875185742
#Sta/Elev= 30
       0  937.35     9.8  930.08    14.8  927.67    35.4  925.17   101.4  907.18
   134.5  885.58   151.1  878.54   159.4  873.74   177.8  856.26   213.2  829.86
   221.5  827.13   242.2  825.31   258.8  821.16   262.9  820.21  269.03821.2145
   275.3  824.44   283.6  825.87   308.3  824.56   337.2  829.45   358.2  835.48
   366.1  839.54   382.6  853.77   394.9  866.72   399.1  869.76     432  884.11
   460.5  902.28   469.1   905.6   477.4  906.49   502.1  913.23   518.8  915.09
#Mann= 5 ,-1,0
       0      .1       0  172.52     .06       0   258.8    .045       0
  269.03     .06       0  272.52      .1       0
#XS Ineff= 2 , 0
                          291.41          834.12
Permanent Ineff=
       F       F
Bank Sta=258.8,269.03
XS Rating Curve= 0 ,0
Exp/Cntr(USF)=0,0
Exp/Cntr=0.3,0.1

Type RM Length L Ch R = 1 ,11728   ,41.9,42,42
XS GIS Cut Line= 3
1602819.50380645 416557.144470251602468.32790748 416706.40623837
 1602428.6418291416764.689535262
#Sta/Elev= 30
       0  928.07    16.7  922.23    29.8  920.69    44.8  915.25    66.2   912.6
      95  901.02   112.3  887.62   131.4  878.66   142.8  870.92   151.5  862.41
   168.8  841.14   186.2  826.52   191.2  823.88   212.3  817.35     221  816.78
   225.4817.3553     234  820.68   238.4  821.24   252.2  821.12   264.5  819.67
   277.5  823.21   316.3  827.11   329.7  831.18     347  838.54   356.4  844.09
   381.6  865.18   388.8  870.22   422.9  887.59   445.9  901.51   452.1  903.91
#Mann= 5 ,-1,0
       0      .1       0   212.3    .045       0   225.4      .1       0
     230     .06       0     250      .1       0
Bank Sta=212.3,225.4
XS Rating Curve= 0 ,0
Exp/Cntr(USF)=0,0
Exp/Cntr=0.3,0.1

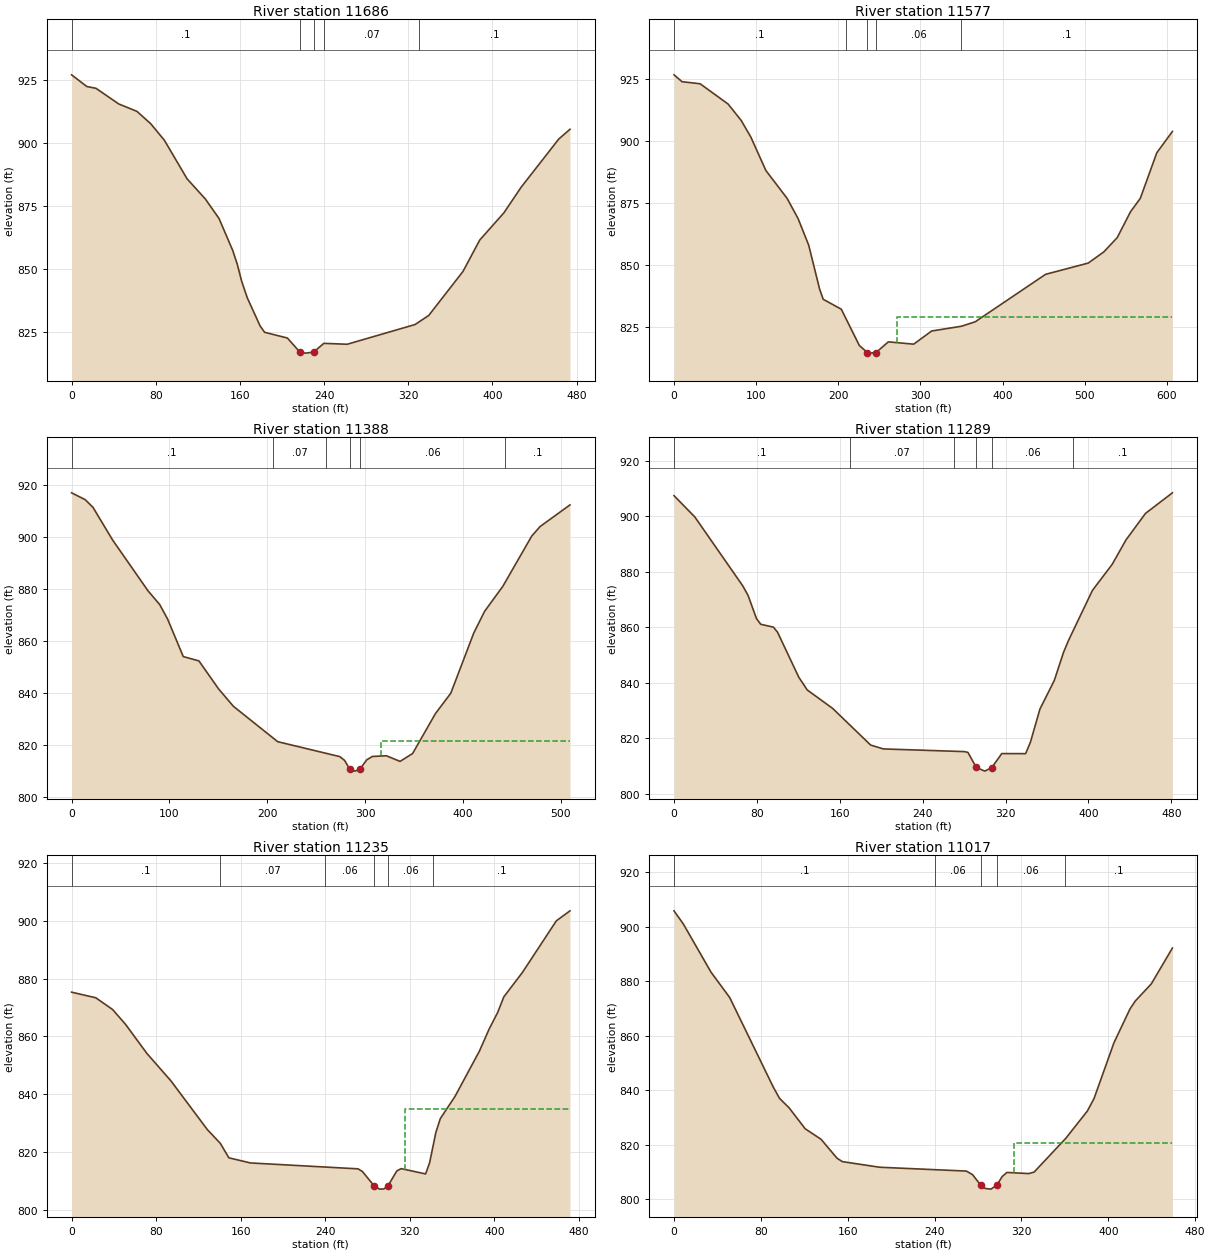
Type RM Length L Ch R = 1 ,11686   ,109.3,109.1,108.8
XS GIS Cut Line= 3
1602805.51615799416519.4255788641602441.84905014416670.796740572
 1602399.5348229416738.612132434
#Sta/Elev= 30
       0  927.24    14.5  922.59    23.2  921.88    44.8  915.66    62.2  912.69
    75.2   907.8    88.2  901.22   109.8  885.87   127.2  877.83   140.2  870.06
   153.2  857.36   157.5  851.91   161.8  844.96   167.1  838.47   179.2  827.36
   183.5  824.82   205.2  822.53  217.05816.9212   222.5  816.53   230.1816.9326
   239.8  820.42     262  820.06   326.5   827.9   339.5  831.51   372.1  849.04
     388  861.51     411  872.36   427.4  882.55   463.2  901.73   473.8  905.58
#Mann= 5 ,-1,0
       0      .1       0  217.05    .045       0   230.1      .1       0
     240     .07       0     330      .1       0
Bank Sta=217.05,230.1
XS Rating Curve= 0 ,0
Exp/Cntr(USF)=0,0
Exp/Cntr=0.3,0.1

Type RM Length L Ch R = 1 ,11577   ,189.8,188.6,187.4
XS GIS Cut Line= 3
  1602773.017795416404.8946374341602284.97316372416630.505373544
1602278.88607008416699.492434805
#Sta/Elev= 30
       0  926.51     9.8  923.74    31.8  922.91    65.9  914.73    81.8  908.14
    93.5  901.47   111.9  887.95   137.6   876.8   151.1   868.6     164   857.9
   177.3  840.19   181.7  836.08   203.7  832.08   225.7  817.45   235.5  814.63
   238.5  814.39  245.98814.6256     261  818.93   291.8     818   313.8  823.31
     350  825.22   366.8  827.02   452.5  846.14   504.4  850.67   523.4  855.18
   539.7  860.93   555.8   871.3   567.8  876.74   587.9  895.12   606.9  903.69
#Mann= 5 ,-1,0
       0      .1       0     210     .06       0   235.5    .045       0
  245.98     .06       0     350      .1       0
#XS Ineff= 2 , 0
                          271.37          828.82
Permanent Ineff=
       F       F
Bank Sta=235.5,245.98
XS Rating Curve= 0 ,0
Exp/Cntr(USF)=0,0
Exp/Cntr=0.3,0.1

Type RM Length L Ch R = 1 ,11388   ,96.4,99.7,103.2
XS GIS Cut Line= 5
1602685.95611524416307.9513731471602520.97133534416297.708385006
1602462.40649185416344.5609815871602375.18873721416415.146469698
1602227.34586415416467.070660061
#Sta/Elev= 30
       0  916.92    13.9   914.3    21.9  911.31    41.9  898.79      78  879.29
      90  873.98      98  868.47   114.1  853.96   130.1   852.3   150.1  841.58
   165.3  834.85   210.6  821.24   274.1  815.49   278.9  814.05  283.94810.8698
   289.6  809.92   294.7  810.75   301.6  814.28   307.3  815.56   321.6  815.83
   335.6  813.66   348.4  816.69   371.7  832.02   387.4  839.86   410.9  863.02
   421.9  871.32   440.6  880.98   470.2  900.34   478.7  903.97   509.2  912.28
#Mann= 6 ,-1,0
       0      .1       0   205.3     .07       0   260.3     .06       0
  283.94    .045       0   294.7     .06       0   442.5      .1       0
#XS Ineff= 2 , 0
                          315.86          821.62
Permanent Ineff=
       F       F
Bank Sta=283.94,294.7
XS Rating Curve= 0 ,0
Exp/Cntr(USF)=0,0
Exp/Cntr=0.3,0.1

Type RM Length L Ch R = 1 ,11289   ,54.4,54,54.1
XS GIS Cut Line= 3
1602658.19029903416236.5797671131602348.80665745416298.800255031
1602205.11514391416380.958799853
#Sta/Elev= 30
       0   907.5    20.1  899.83    66.3  875.02    71.5  871.52    79.6  863.19
    83.7  861.13      96  860.09     100  858.23   120.4  842.07   128.6  837.44
   153.1   830.8   189.8  817.58     202  816.18   280.3  815.21   283.7  814.93
   291.8  809.48     300  808.17  306.75 809.455   316.4   814.5   339.4  814.47
     344  818.56   353.2  830.53   367.1  840.88     376  851.01   380.9  855.37
   403.9  873.35   422.9   882.7   436.2  891.49   455.1  901.11   481.1  908.53
#Mann= 6 ,-1,0
       0      .1       0     170     .07       0     270     .06       0
   291.8    .045       0  306.75     .06       0  385.58      .1       0
Bank Sta=291.8,306.75
XS Rating Curve= 0 ,0
Exp/Cntr(USF)=0,0
Exp/Cntr=0.3,0.1

Type RM Length L Ch R = 1 ,11235   ,221.7,217.8,211.6
XS GIS Cut Line= 3
1602626.22065607416192.578538087 1602319.9308509 416251.70518959
1602182.08325059416332.144936402
#Sta/Elev= 30
       0  875.28    22.9  873.34    38.8  869.28      51  864.17    71.4  854.01
      94  844.58   128.4  827.74   140.7  822.97   148.8  817.95   169.2  816.18
     271  814.14   275.1  813.23  286.15 808.286   291.4  807.12   295.5  807.19
   299.5  808.36   307.7  813.43   311.8  814.21   334.9  812.38   338.7  816.23
   344.6   826.7   348.8  831.51   362.7  839.18   385.8  854.87   395.1  862.58
   403.1  868.25   408.9  873.65   426.5  882.11   458.6  899.97   471.5  903.43
#Mann= 6 ,-1,0
       0      .1       0     140     .07       0     240     .06       0
  286.15    .045       0   299.5     .06       0  341.94      .1       0
#XS Ineff= 2 , 0
                          315.73          834.68
Permanent Ineff=
       F       F
Bank Sta=286.15,299.5
XS Rating Curve= 0 ,0
Exp/Cntr(USF)=0,0
Exp/Cntr=0.3,0.1

Type RM Length L Ch R = 1 ,11017   ,234.4,236.1,238
XS GIS Cut Line= 2
1602349.13029717415866.0552522851602083.32720819416240.411511186
#Sta/Elev= 30
       0  905.87     8.7  900.97    34.1  883.35    51.3  874.05    91.4  841.21
    97.2  837.04   106.1  833.52   120.8  825.89   135.5     822   150.2  815.05
   155.1  813.81   189.5  811.75   269.3  810.35     275  809.04  282.45805.2116
   286.5  803.99   291.9  803.72   297.4  805.19   302.3  808.34   306.6  809.84
   326.8  809.43   331.7  809.97     361  822.42   380.8  832.42   386.9  836.97
   405.3  857.49     420  869.83   424.9  872.77   439.7  879.08   459.1  892.22
#Mann= 5 ,-1,0
       0      .1       0     240     .06       0  282.45    .045       0
   297.4     .06       0     360      .1       0
#XS Ineff= 2 , 0
                          313.33          820.74
Permanent Ineff=
       F       F
Bank Sta=282.45,297.4
XS Rating Curve= 0 ,0
Exp/Cntr(USF)=0,0
Exp/Cntr=0.3,0.1

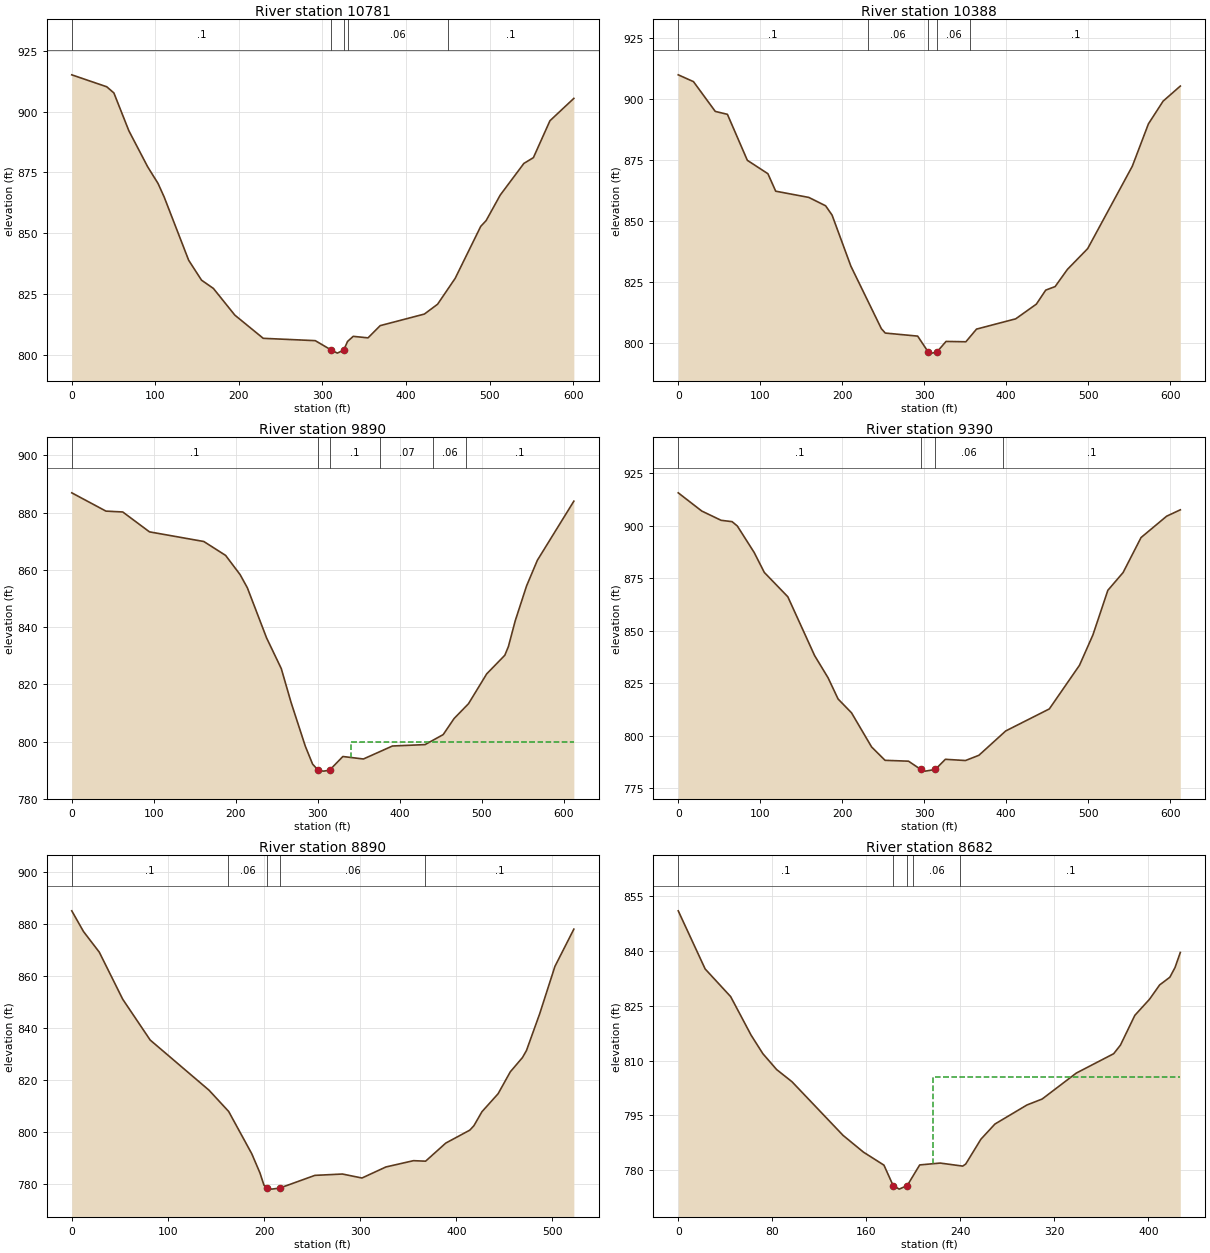
Type RM Length L Ch R = 1 ,10781   ,394.3,392.9,390.5
XS GIS Cut Line= 2
 1602239.8406768415745.2400098881601784.49009621 416137.20050573
#Sta/Elev= 30
       0  915.17    41.9  910.25    50.4  907.72    68.3  892.18    90.9   877.3
   103.2  870.52   110.5  864.98   139.9   838.9   155.3  830.71   169.5  827.31
   195.1  816.35   229.1   806.8   291.4  805.84  310.46 801.992   317.8  800.71
   325.5  801.99     330  805.51   336.8  807.61   354.5  806.99   369.1  812.02
   421.9  816.77   437.7   820.8   458.8  831.47   489.4  852.85   495.8   855.2
   512.7  865.71     541  878.73   552.4  881.11   572.2  896.28   600.8  905.48
#Mann= 5 ,-1,0
       0      .1       0  310.46    .045       0   325.5     .07       0
     330     .06       0     450      .1       0
Bank Sta=310.46,325.5
XS Rating Curve= 0 ,0
Exp/Cntr(USF)=0,0
Exp/Cntr=0.3,0.1

Type RM Length L Ch R = 1 ,10388   ,499.2,498.3,497.3
XS GIS Cut Line= 6
1601885.43782951415479.8494564291601830.57901534415555.872926429
1601779.25956418 415626.743191511601735.27146317415687.488476843
1601676.62066184415768.4830655011601526.32765535415976.030878752
#Sta/Elev= 30
       0  909.85    18.6  907.06    45.2  894.86      60  893.67    84.3  874.83
   109.4  869.34   118.9  862.18   159.3  859.63   179.8   856.2   187.7  852.37
   210.6  831.48   247.8  805.86   252.6  804.06   292.1  802.81   305.1  796.24
   309.4  795.84  315.41796.2294   326.7  800.63   350.9  800.49   363.9  805.68
   411.7  809.89   436.9  815.91   448.3  821.65   459.8  823.11   474.8  830.15
   499.5  838.66   553.9  872.38   573.6  889.76   591.5  899.06   612.5  905.25
#Mann= 5 ,-1,0
       0      .1       0  231.25     .06       0   305.1    .045       0
  315.41     .06       0  356.25      .1       0
Bank Sta=305.1,315.41
XS Rating Curve= 0 ,0
Exp/Cntr(USF)=0,0
Exp/Cntr=0.3,0.1

Type RM Length L Ch R = 1 ,9890    ,501.2,500,498
XS GIS Cut Line= 6
1601398.67272693415226.8289650831601321.27819668415390.724306583
1601289.25267017415458.5430685881601246.55098392415548.967428416
1601214.52578551415616.7858623421601137.13092718415780.680875748
#Sta/Elev= 30
       0  886.94    41.7  880.55    62.2  880.25    94.8   873.3   161.1  869.93
   187.7  865.07   205.4  858.34   214.2  853.76   237.6  836.28   255.6  825.51
   267.6  813.63     285  798.33   293.8  792.14   300.7  789.99   307.1  789.69
  314.45789.9956   330.7   794.8   355.8  793.93   391.2  798.47     431  798.96
   453.1  802.45   466.4  808.07     484  813.25   506.2  823.68   528.3  830.18
   532.7  833.25     541  842.23   554.8  854.39     568  863.37   612.5  884.02
#Mann= 6 ,-1,0
       0      .1       0   300.7    .045       0  314.45      .1       0
  376.25     .07       0  441.25     .06       0  481.25      .1       0
#XS Ineff= 1 ,-1
  341.19612.4998   799.7
Permanent Ineff=
       F
Bank Sta=300.7,314.45
XS Rating Curve= 0 ,0
Exp/Cntr(USF)=0,0
Exp/Cntr=0.3,0.1

Type RM Length L Ch R = 1 ,9390    ,503.7,500,498
XS GIS Cut Line= 6
1600855.46876083 415077.838121341600835.79065059415169.499683425
1600817.47802317415255.062176332 1600801.8455085415328.414719924
1600781.00139008415426.2180020061600727.58975151415676.840204179
#Sta/Elev= 30
       0   915.7    28.7  907.02    52.3   902.6    65.7  901.96    72.1  899.88
    92.7  887.23     105  877.76   133.7  866.15   166.4   838.1   182.8  827.54
     195  817.44   211.4  810.84   235.9  794.57   252.3   788.2   280.9  787.79
  295.99783.8315   301.4  783.05   313.6  783.84   325.9  788.69   350.4   788.1
   366.8   790.6   399.5   802.2   452.7   812.7   489.5   833.5   505.9  847.99
   524.1  869.23   542.7  877.71   564.6  894.38   595.8  904.56   612.5   907.6
#Mann= 4 ,-1,0
       0      .1       0  295.99    .045       0   313.6     .06       0
  396.25      .1       0
Bank Sta=295.99,313.6
XS Rating Curve= 0 ,0
Exp/Cntr(USF)=0,0
Exp/Cntr=0.3,0.1

Type RM Length L Ch R = 1 ,8890    ,210.2,207.6,207.3
XS GIS Cut Line= 6
1600263.03720292415112.5326057521600294.90590559415271.877103344
1600314.51708683415369.9353061771600329.95898509415443.332141012
1600356.16956259415528.0471946751600386.12291476415619.419387251
#Sta/Elev= 30
       0  885.11    12.2  877.14    28.6  869.22      53  851.09    81.6  835.37
   142.8  816.07   163.2   807.9   187.3  791.58   195.8  784.21   199.9  779.56
  203.05778.3998     208     778   216.2  778.39   252.9  783.29   281.5  783.81
   301.9  782.28   326.8  786.53   355.5  788.95   368.1  788.76     389   795.7
   414.1  800.71   418.3  802.39   426.7  807.79   443.5  814.71   456.2  823.15
   468.8  828.61     473  831.33   486.8  845.53   502.6   863.7   522.3  878.06
#Mann= 5 ,-1,0
       0      .1       0   162.5     .06       0  203.05    .045       0
   216.2     .06       0   367.5      .1       0
Bank Sta=203.05,216.2
XS Rating Curve= 0 ,0
Exp/Cntr(USF)=0,0
Exp/Cntr=0.3,0.1

Type RM Length L Ch R = 1 ,8682    ,218.4,218.5,218
XS GIS Cut Line= 2
 1600052.0496266415247.4269285991600218.63058425415640.708287276
#Sta/Elev= 30
       0   850.9    22.9  835.02    44.6  827.46      62  816.93      72  811.87
    83.7  807.54    96.8   804.2   140.2  789.56   157.6  784.97     175  781.42
   182.8  775.85     188  774.87  194.84775.8578   205.4  781.48   222.8  781.99
     242  781.16   244.5   781.7   257.5  788.52   269.4  792.65   296.6  797.85
   309.6  799.49   338.6  806.57   370.4  811.86   376.2  814.23   388.4  822.34
   400.9  826.74   409.5  830.65   418.2  832.76   422.6  835.41   427.1  839.52
#Mann= 5 ,-1,0
       0      .1       0   182.8    .045       0  194.84      .1       0
     200     .06       0     240      .1       0
#XS Ineff= 2 , 0
                          216.72          805.57
Permanent Ineff=
       F       F
Bank Sta=182.8,194.84
XS Rating Curve= 0 ,0
Exp/Cntr(USF)=0,0
Exp/Cntr=0.3,0.1

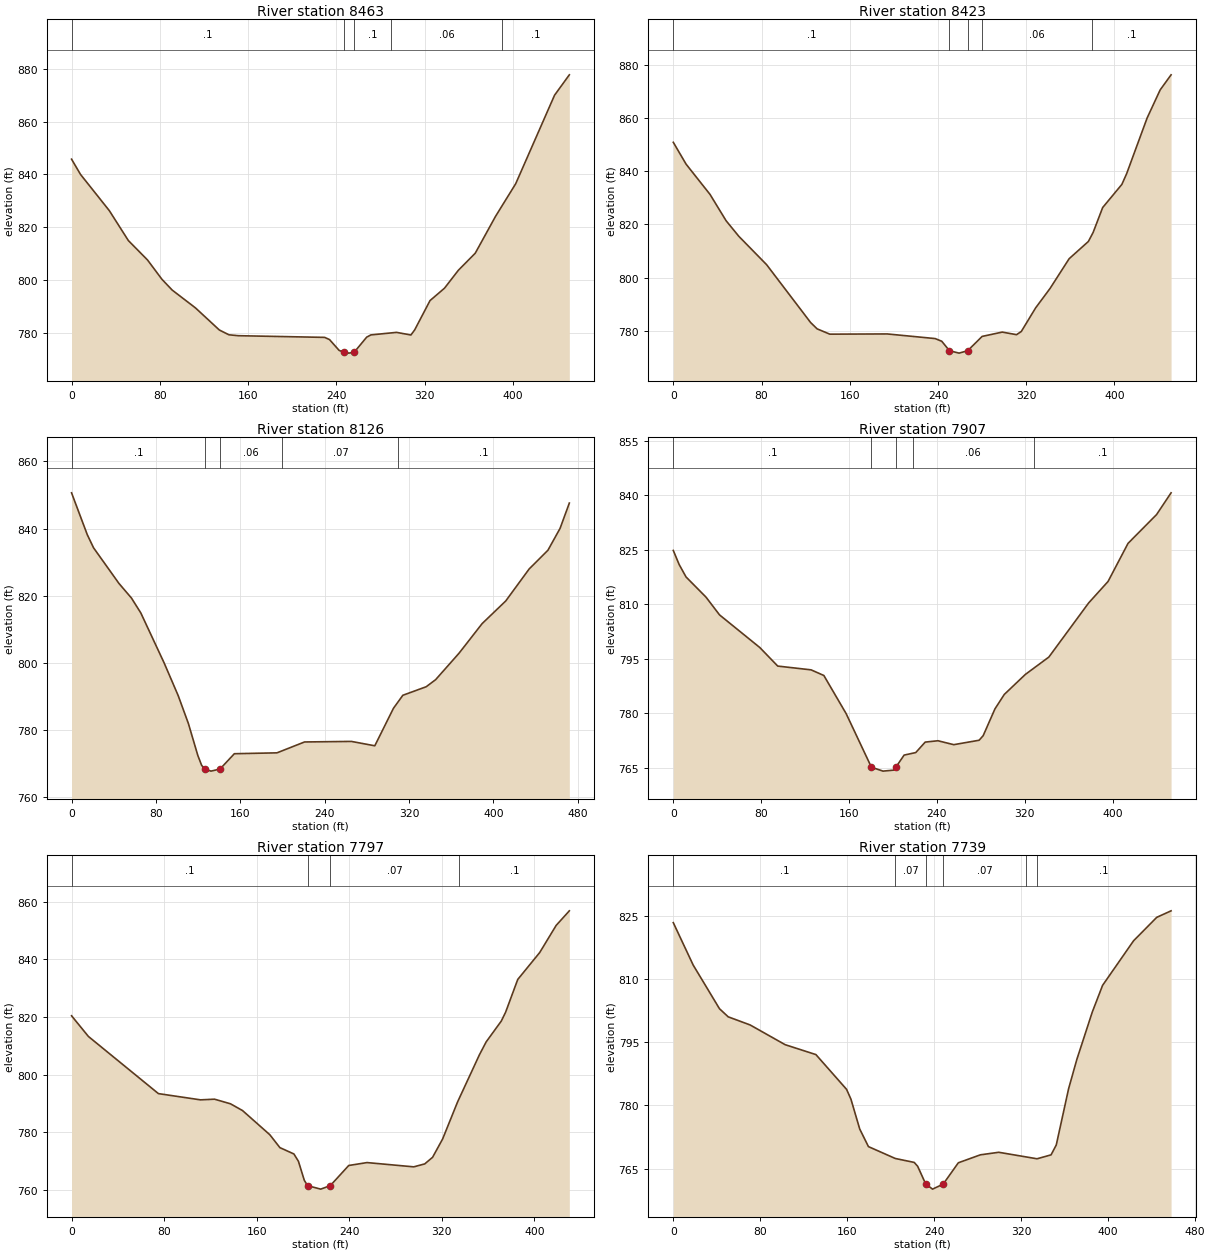
Type RM Length L Ch R = 1 ,8463    ,40.6,40.4,40.5
XS GIS Cut Line= 2
1599844.13655163415305.0413951571600019.48492811415720.867545095
#Sta/Elev= 30
       0  845.76     8.1  839.99    34.2  826.26    51.5  814.89    68.9  807.51
    81.9  800.22    91.2  796.12   112.3  789.36     134  780.96   142.7  779.14
   151.4   778.8   229.5  778.16   233.9  777.32   242.6  773.22   246.9   772.5
   251.2  772.19  256.16  772.48   267.6  778.26   271.4   779.1   294.6  780.06
   307.7  779.07   311.1  781.01     325  792.12   338.1  796.81   350.7  803.62
     366  810.09   384.3     824   402.7  836.46   437.9  870.02   451.3  877.75
#Mann= 5 ,-1,0
       0      .1       0   246.9    .045       0  256.16      .1       0
     290     .06       0     390      .1       0
Bank Sta=246.9,256.16
XS Rating Curve= 0 ,0
Exp/Cntr(USF)=0,0
Exp/Cntr=0.3,0.1

Type RM Length L Ch R = 1 ,8423    ,294,297.3,295
XS GIS Cut Line= 2
1599804.05692272415313.808813981 1599979.4052992415729.634963919
#Sta/Elev= 30
       0  850.86    11.6  842.65    33.3  831.28    47.9  821.37    59.4  815.54
    84.6  804.87   124.5  783.13   130.4  780.75   141.9  778.76     194  778.84
   237.4   777.1   243.4  776.09   250.4  772.53   259.1  771.63   266.9  772.54
     280  777.91   298.2  779.53   311.2  778.57   315.5  779.76   328.5  788.63
   341.6  795.95   358.9  807.12   376.3  813.58   380.6  816.95   389.3  826.35
   406.7  835.05     411  839.05   429.6  860.01   441.4  870.55   451.3  876.22
#Mann= 5 ,-1,0
       0      .1       0   250.4    .045       0   266.9      .1       0
     280     .06       0     380      .1       0
Bank Sta=250.4,266.9
XS Rating Curve= 0 ,0
Exp/Cntr(USF)=0,0
Exp/Cntr=0.3,0.1

Type RM Length L Ch R = 1 ,8126    ,220.9,218.3,213.7
XS GIS Cut Line= 2
1599579.39306784 415389.355157011599783.91941417415814.843002493
#Sta/Elev= 30
       0  850.65    14.9  838.21    20.9  834.27    44.9  823.71    56.8  819.34
    65.7   814.9    87.9  799.97   101.2  790.25   110.8  782.01   119.8  772.45
   123.4  769.53  126.64768.4516   132.2  767.83   140.8  768.45   154.4  773.01
   194.8  773.27     221  776.51   265.4  776.67   287.6  775.37   305.3  786.53
   314.2   790.4   336.4  792.95   345.3  795.05   367.5  802.92   389.4  811.73
   411.8  818.47     434  827.99   451.8  833.56   463.3  840.06   472.1   847.6
#Mann= 5 ,-1,0
       0      .1       0  126.64    .045       0   140.8     .06       0
     200     .07       0     310      .1       0
Bank Sta=126.64,140.8
XS Rating Curve= 0 ,0
Exp/Cntr(USF)=0,0
Exp/Cntr=0.3,0.1

Type RM Length L Ch R = 1 ,7907    ,105.8,110.5,114.8
XS GIS Cut Line= 3
1599435.57243154415531.3345725421599459.31449963415646.948184502
1599738.71209774 415832.30018586
#Sta/Elev= 30
       0   824.8     5.3  820.95    11.6  817.51    29.8  811.95    42.1  807.07
    78.8  798.08    95.1  792.98   125.5  791.94   137.1  790.39   157.4   779.9
   180.4  765.15     191  764.07   200.6  764.34  202.73765.1792   210.2  768.48
   220.8  769.18   229.4  772.06     241  772.43   255.4  771.35   278.5  772.57
   282.2  773.83   292.9  781.19   301.4  785.17   320.6  790.68     342  795.46
   378.2  810.34   395.9  816.26   414.1  826.75   440.1  834.68   453.3  840.66
#Mann= 5 ,-1,0
       0      .1       0   180.4    .045       0  202.73      .1       0
  218.03     .06       0  328.03      .1       0
Bank Sta=180.4,202.73
XS Rating Curve= 0 ,0
Exp/Cntr(USF)=0,0
Exp/Cntr=0.3,0.1

Type RM Length L Ch R = 1 ,7797    ,58.3,58.3,58.3
XS GIS Cut Line= 3
1599405.65226016415554.0799595121599431.86755111415747.385229573
1599557.56336525 415946.15152997
#Sta/Elev= 30
       0  820.43    14.6  813.25    75.1  793.45   111.5  791.29   123.6  791.52
   137.4  789.92   147.8  787.58   171.4   779.2   180.1  774.73   192.2  772.54
   196.1  770.02   201.2  763.41  203.99 761.553   215.4  760.35   223.7  761.57
   239.6  768.54   255.4  769.55   295.8  768.07   305.3  769.09   312.1  771.38
   320.8  777.76   333.7  790.57   352.6  806.93   358.4  811.37   371.5  818.61
   375.2  821.65   385.7  833.01   404.7  842.35   418.9  851.74   430.3   856.8
#Mann= 4 ,-1,0
       0      .1       0  203.99    .045       0   223.7     .07       0
  335.07      .1       0
Bank Sta=203.99,223.7
XS Rating Curve= 0 ,0
Exp/Cntr(USF)=0,0
Exp/Cntr=0.3,0.1

Type RM Length L Ch R = 1 ,7739    ,147.7,155.4,163.5
XS GIS Cut Line= 3
1599343.83651904415562.3771843071599367.72317038415755.100294464
1599509.13730193415977.735150928
#Sta/Elev= 30
       0  823.36    18.3   813.3    42.5  802.94    50.5  801.02    70.7  799.09
   102.9  794.41   131.2  792.06   159.4  783.81   163.4  781.49   171.5   774.4
   179.5  770.23   204.2  767.41   221.6  766.48   224.8  765.56   232.2  761.36
   238.5  760.14  248.27761.3293   262.2  766.39   282.5  768.28   299.4  768.88
   334.6  767.34   347.5  768.27   352.3  770.62   363.6  783.92   371.2   790.9
   385.4  802.14   394.9  808.49   423.4  819.06   444.7  824.62   457.9  826.17
#Mann= 6 ,-1,0
       0      .1       0   204.2     .07       0   232.2    .045       0
  248.27     .07       0   324.2     .06       0   334.2      .1       0
Bank Sta=232.2,248.27
XS Rating Curve= 0 ,0
Exp/Cntr(USF)=0,0
Exp/Cntr=0.3,0.1