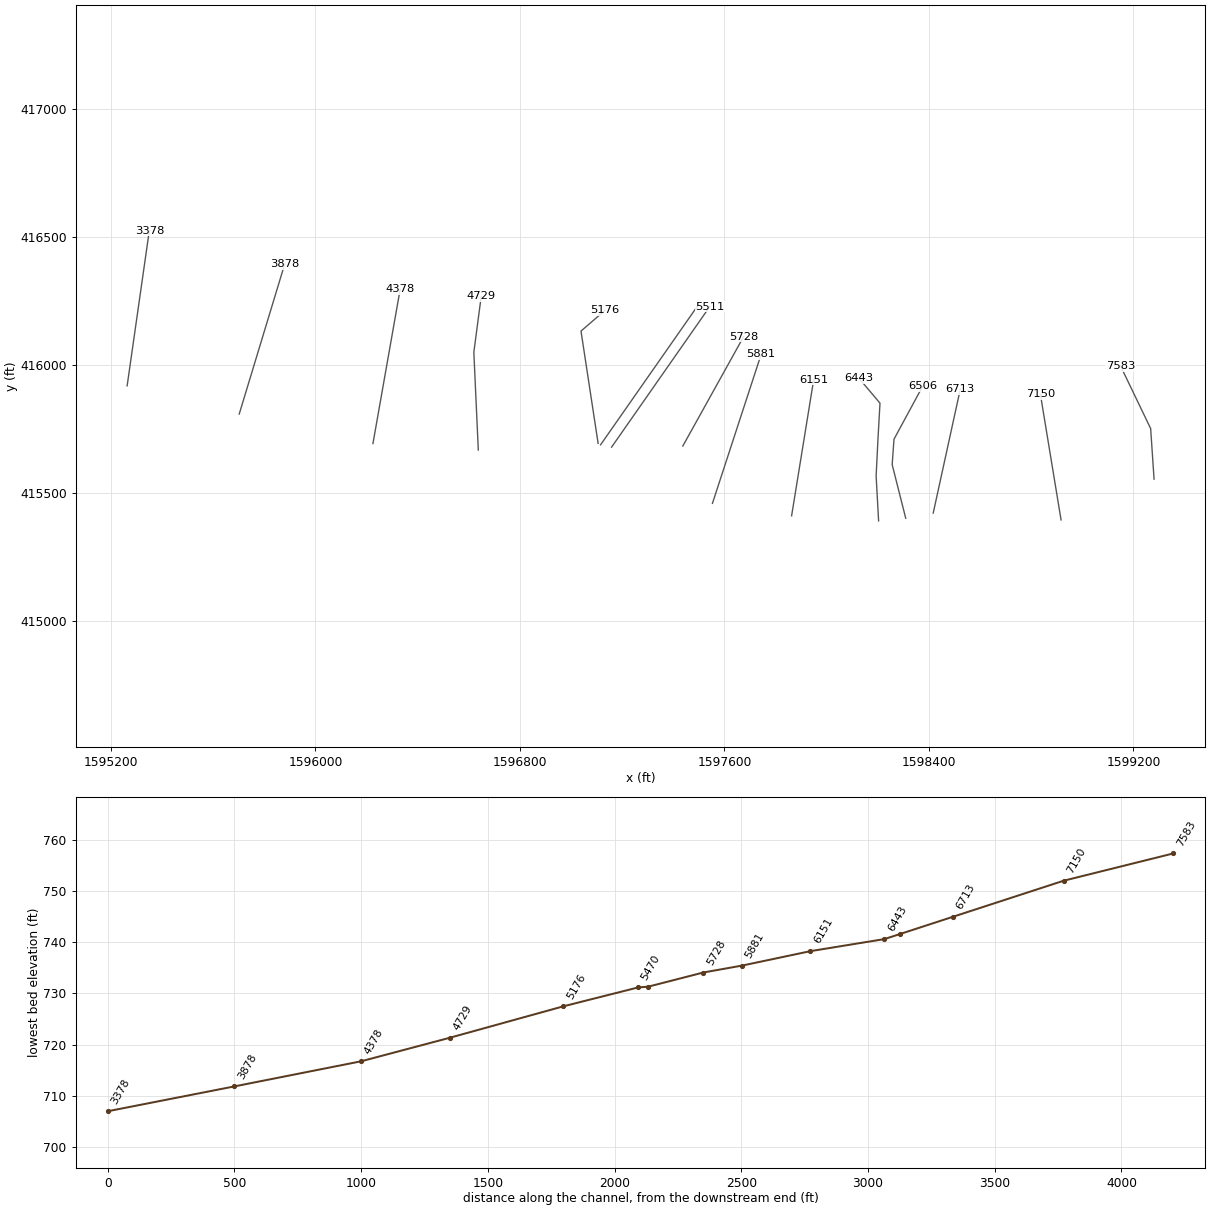
HEC-RAS study DOOLINRN.prj: DOOLINRN

--- DOOLINRN.g01 (geometry) --- (continued)

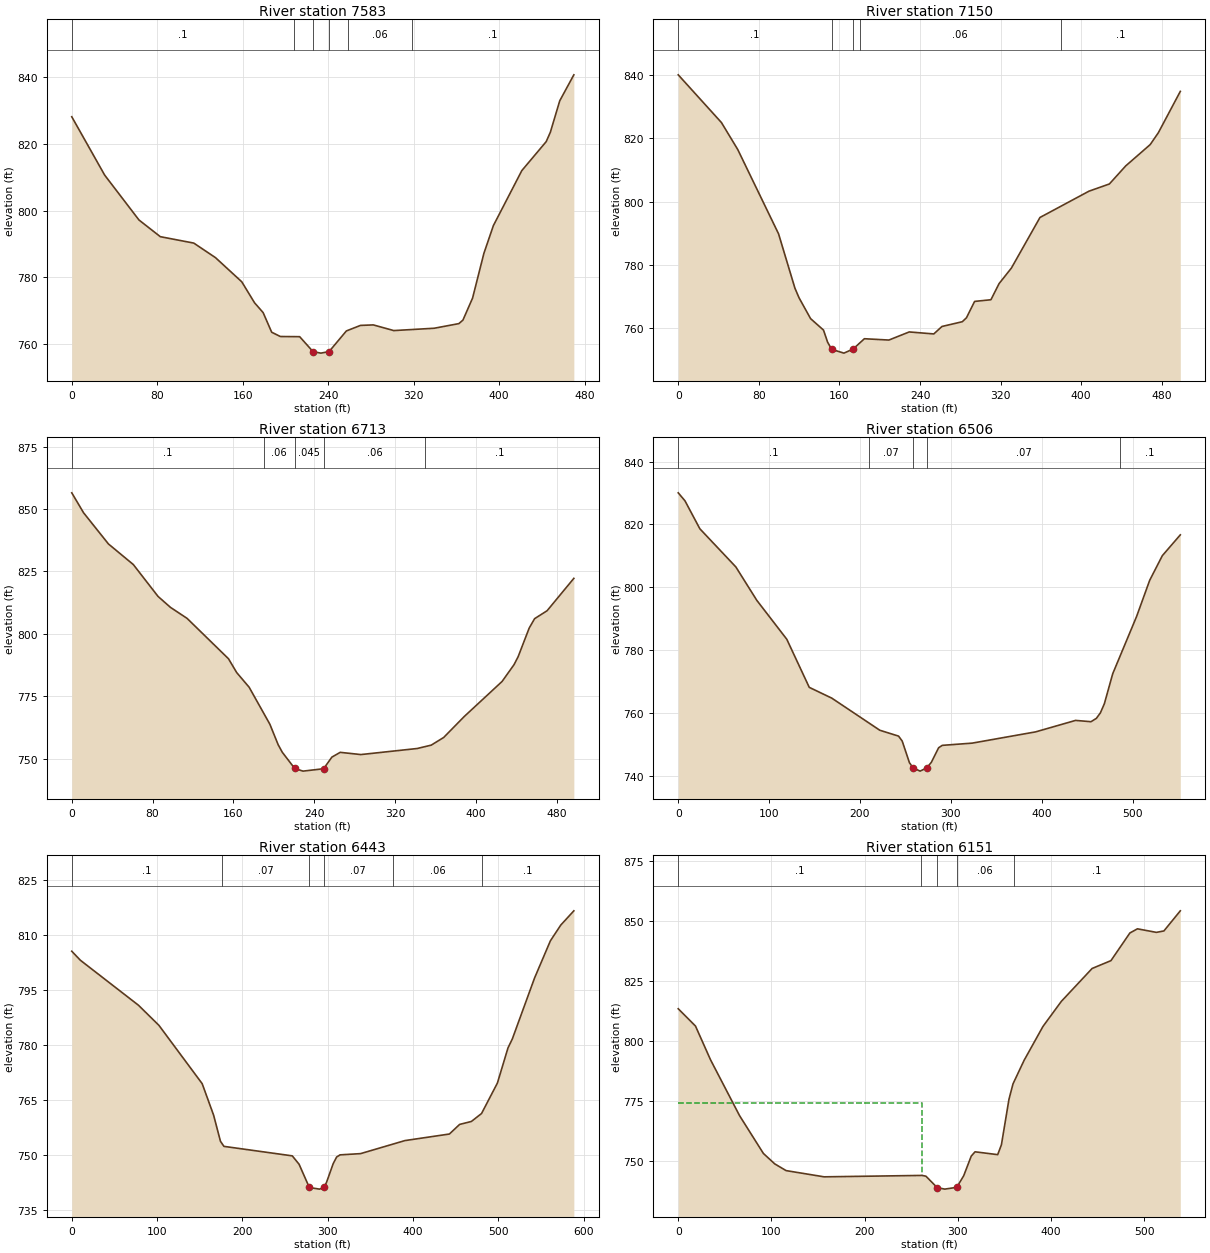
Type RM Length L Ch R = 1 ,7583    ,438,433.4,430.9
XS GIS Cut Line= 3
1599280.62465438415553.8179038471599267.25959783415751.645777625
1599149.47433588 415996.34694198
#Sta/Elev= 30
       0  828.18    30.8  810.68    62.9  797.23    82.9  792.22   114.2   790.3
   134.5  785.94   159.1   778.7   171.1  772.39   179.1  769.46   187.1  763.58
   195.2  762.29   213.3  762.24225.8977757.7305   233.2  757.31  240.81757.7677
     257  763.96   270.2  765.62   282.2  765.77   301.4  764.07   339.2  764.77
   362.3  766.16   366.1  767.21   375.1  773.79   385.7  787.21   394.6  795.55
   421.2  812.03     444  820.71   447.9  823.52   456.7  832.96   469.9  840.75
#Mann= 6 ,-1,0
       0      .1       0  208.28     .07       0225.8977    .045       0
  240.81     .07       0  258.28     .06       0  318.28      .1       0
Bank Sta=225.8977,240.81
XS Rating Curve= 0 ,0
Exp/Cntr(USF)=0,0
Exp/Cntr=0.3,0.1

Type RM Length L Ch R = 1 ,7150    ,441.8,437,434
XS GIS Cut Line= 2
1598916.80823881 415394.232724651598835.94339419415885.982114545
#Sta/Elev= 30
       0  840.13    42.9  825.01    59.1  816.46    99.6  789.76   115.8  772.59
   119.9  769.52   131.4   762.9   144.2  759.28   148.3  755.44   152.3  753.18
   164.5  751.98   173.6  753.28   184.8  756.54   209.1  756.12   229.3  758.69
   253.7  758.06   261.8  760.42     282  761.93   286.1  763.17   294.2  768.36
   310.4  768.89   318.5     774   330.7  778.91   359.1  794.95   407.7  803.27
     428  805.56   444.2  811.28   468.5  818.03   476.6  821.79   498.4  834.88
#Mann= 5 ,-1,0
       0      .1       0   152.3    .045       0   173.6      .1       0
     180     .06       0     380      .1       0
Bank Sta=152.3,173.6
XS Rating Curve= 0 ,0
Exp/Cntr(USF)=0,0
Exp/Cntr=0.3,0.1

Type RM Length L Ch R = 1 ,6713    ,205.6,207.3,210.1
XS GIS Cut Line= 2
1598416.72076025415421.0610279181598522.82684445415906.358031265
#Sta/Elev= 30
       0  856.51    11.7   848.5    36.3  836.01    60.9  827.76    85.4  814.97
    97.7  810.58   114.1  806.18   155.1  789.98   163.2  784.45   175.5  778.58
     196  763.76   204.2  755.56   208.3  752.51   220.6  746.01   228.8  744.94
   249.2   745.9   257.4  750.56   265.6  752.47   286.1  751.58   341.8  754.01
   355.7  755.36     368  758.43   388.4  766.85   425.8  780.89   437.6  787.61
   441.7  790.83   452.6  802.28     458  806.07   470.3  809.23   496.8  822.22
#Mann= 5 ,-1,0
       0      .1       0     190     .06       0   220.6    .045       0
   249.2     .06       0     350      .1       0
Bank Sta=220.6,249.2
XS Rating Curve= 0 ,0
Exp/Cntr(USF)=0,0
Exp/Cntr=0.3,0.1

Type RM Length L Ch R = 1 ,6506    ,63.1,62.9,63.8
XS GIS Cut Line= 4
1598309.25304667415400.725267855 1598256.1989562415610.491860796
1598263.30056544415709.914390261 1598375.9117978 415917.89008965
#Sta/Elev= 30
       0  830.06     7.4  827.53    23.8  818.63    63.4  806.51    86.5  795.88
   119.5  783.51   144.2  768.23     169   764.8   221.9  754.59   242.5  752.73
   246.5  751.16   254.5  744.26   258.5  742.64   266.2   741.6  273.57742.6451
   278.6  744.41   286.6  749.03   290.6  749.79   323.6   750.5   393.4  754.08
   437.3  757.72   454.3  757.31   460.2  758.37   464.6   760.1     469  763.01
   478.2  772.55   504.5  790.77   518.9  802.25   532.8  810.08   552.6   816.7
#Mann= 5 ,-1,0
       0      .1       0     210     .07       0   258.5    .045       0
  273.57     .07       0  486.05      .1       0
Bank Sta=258.5,273.57
XS Rating Curve= 0 ,0
Exp/Cntr(USF)=0,0
Exp/Cntr=0.3,0.1

Type RM Length L Ch R = 1 ,6443    ,293.1,291.6,290.7
XS GIS Cut Line= 5
 1598203.1040161 415390.450578181598193.43261104415566.573179998
1598200.95861486415716.4986633021598208.54508909415850.932059603
1598126.36932495415948.325557853
#Sta/Elev= 30
       0  805.52    10.1  803.06    78.2  790.78   102.2  785.29   152.9  769.37
   166.3  760.77   174.3  753.66   178.4  752.26   258.5  749.67   266.5  747.38
   278.5  741.04   290.5  740.59   295.2  741.05   298.5  742.34   306.5  747.56
   310.5  749.35   314.5  749.94   338.6  750.28   390.6  753.84   442.7  755.63
   454.7  758.25   468.5  759.06   480.4  761.23     499  769.55   511.4  779.14
   516.5  781.59   542.5  798.19   561.1  808.36   573.3  812.67   588.6  816.55
#Mann= 6 ,-1,0
       0      .1       0  176.39     .07       0   278.5    .045       0
   295.2     .07       0   376.5     .06       0  481.15      .1       0
Bank Sta=278.5,295.2
XS Rating Curve= 0 ,0
Exp/Cntr(USF)=0,0
Exp/Cntr=0.3,0.1

Type RM Length L Ch R = 1 ,6151    ,271,270,268.5
XS GIS Cut Line= 2
1597862.80819021  415410.29689771597949.09072467415941.908642267
#Sta/Elev= 30
       0  813.53    18.5  806.31    34.7  792.18    65.8   768.9    91.4  753.11
   103.6  748.76   115.7  745.97   156.5  743.37   261.6  743.96   265.7  743.64
   277.8  738.88   285.9  738.24  298.77738.9938   306.2   743.8   314.3     752
   318.4  753.82   342.7  752.63   346.7  756.76   354.8  775.75   359.1  782.15
     371  791.98   391.3  806.16     411  816.62     444  830.34   464.2  833.61
   484.5  845.15   492.6  846.89   512.9  845.41     521     846   538.6   854.4
#Mann= 5 ,-1,0
       0      .1       0     260     .06       0   277.8    .045       0
  298.77     .06       0     360      .1       0
#XS Ineff= 2 , 0
          261.39  774.11
Permanent Ineff=
       F       F
Bank Sta=277.8,298.77
XS Rating Curve= 0 ,0
Exp/Cntr(USF)=0,0
Exp/Cntr=0.3,0.1

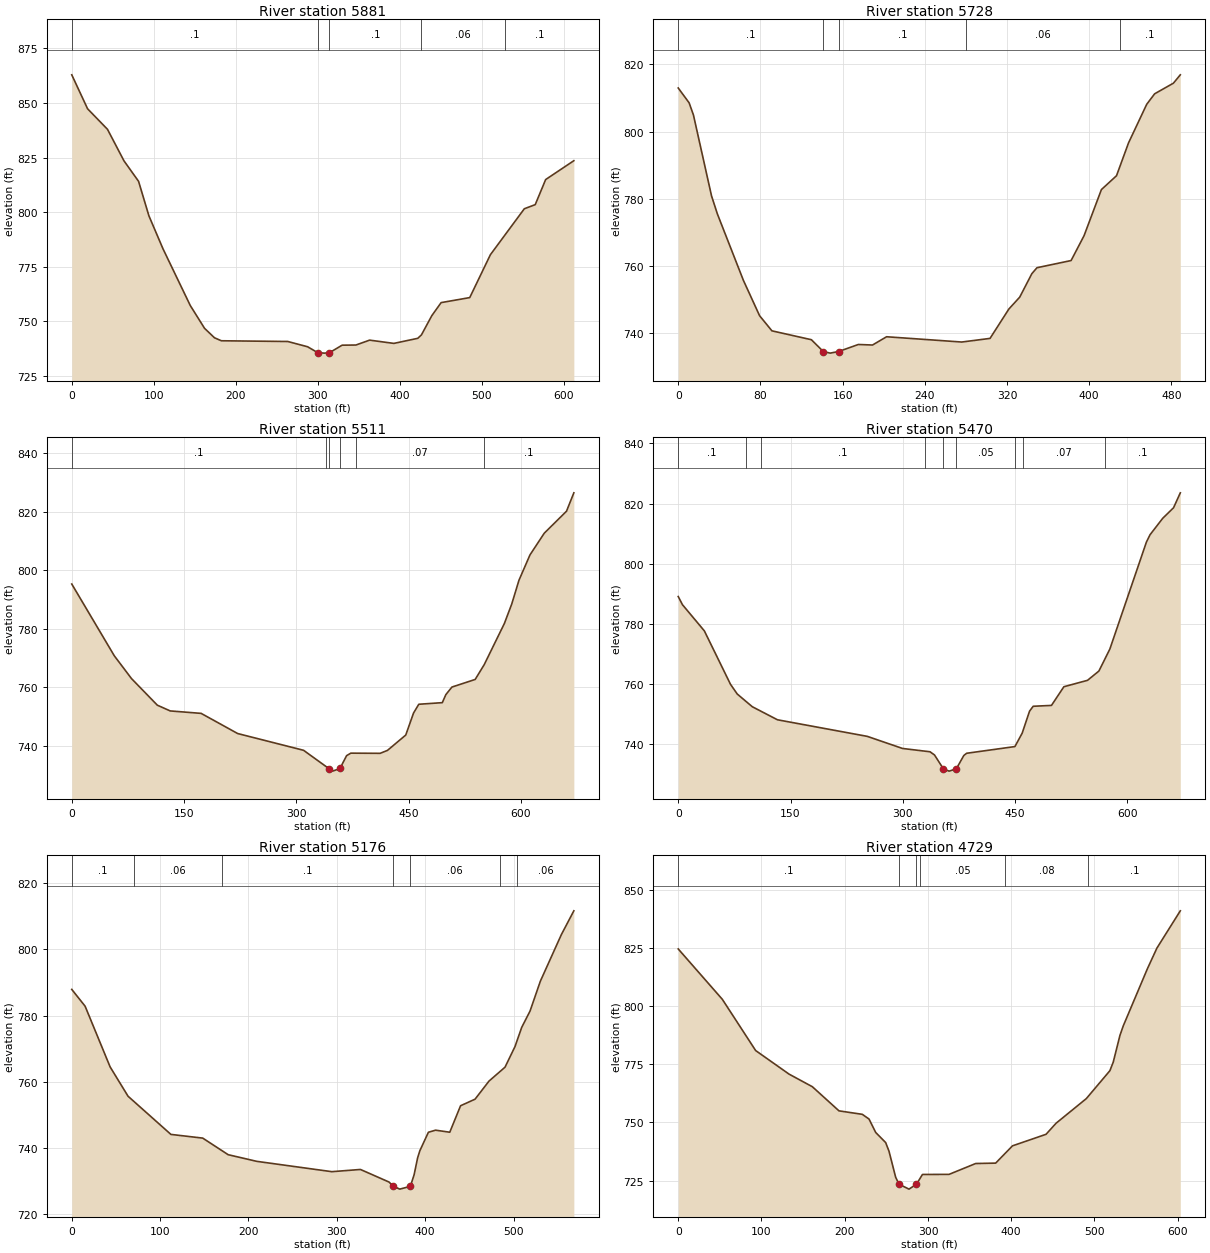
Type RM Length L Ch R = 1 ,5881    ,154.1,153,151.3
XS GIS Cut Line= 6
1597553.18960425 415459.092280091597609.51101393415631.369494587
1597632.81575733415702.6567535851597663.88951409415797.706432253
1597687.19425751415868.9940193441597743.51599526416041.271233842
#Sta/Elev= 30
       0  862.92    19.3  847.36    43.6  837.95    63.7  823.51    81.5  814.13
    94.1  798.33   111.3   783.2   144.6  757.21     162  746.78   174.1  742.45
   182.5  741.08   263.5  740.75   287.7  738.34   300.3  735.58   308.7  735.42
   314.3   735.6   329.8  739.06   346.6  739.13   363.4  741.37   392.9  739.88
   422.1   742.2   426.6  743.79   439.2  752.56   450.6  758.56   485.5  760.86
   510.7  780.51   552.1  801.56   565.4  803.45   578.1  814.93   612.5  823.58
#Mann= 5 ,-1,0
       0      .1       0   300.3    .045       0   314.3      .1       0
  426.25     .06       0  528.75      .1       0
Bank Sta=300.3,314.3
XS Rating Curve= 0 ,0
Exp/Cntr(USF)=0,0
Exp/Cntr=0.3,0.1

Type RM Length L Ch R = 1 ,5728    ,218,217.1,216.2
XS GIS Cut Line= 2
1597437.29483521415683.276009607 1597674.6914872416110.387080061
#Sta/Elev= 30
       0  812.94    10.6  808.53    14.8  804.92    32.4  780.86    38.1  775.48
    63.4  755.74    79.2  745.19    91.2   740.7   129.6  738.06   141.2  734.55
   147.9  734.07  156.15 734.554   175.3  736.64   189.1  736.48   202.8  738.94
     276  737.37   303.5  738.45   321.8  747.18   332.4  750.73   344.2  757.71
   349.2  759.48   382.4  761.61     395     769   411.9  782.72   426.6  786.84
   438.3  796.61     456  808.09   463.7  811.21     482  814.38   488.7  816.86
#Mann= 5 ,-1,0
       0      .1       0   141.2    .045       0  156.15      .1       0
     280     .06       0     430      .1       0
Bank Sta=141.2,156.15
XS Rating Curve= 0 ,0
Exp/Cntr(USF)=0,0
Exp/Cntr=0.3,0.1

Type RM Length L Ch R = 1 ,5511    ,41.1,40.6,40.8
XS GIS Cut Line= 2
1597158.63137673415678.8860775461597542.72782045416228.589321274
#Sta/Elev= 30
       0  795.33    56.8  770.78    79.8  762.97   114.3  753.87   131.5  751.91
   172.8  751.07   221.6  744.17   309.6  738.44  343.52732.1677   348.5  731.31
   358.2  732.21   367.1  736.61   372.7  737.46   411.9   737.4   421.7  738.41
   446.1  743.66   456.5  751.19   463.5  754.19   494.9  754.74   499.7  757.51
   507.8  760.08   538.8  762.68   550.9  767.75   577.8  781.82   587.6  788.45
   597.3  796.62     612  805.29   631.1  812.73   660.8  820.25   670.6  826.54
#Mann= 6 ,-1,0
       0      .1       0     340     .05       0  343.52    .045       0
   358.2     .05       0     380     .07       0     550      .1       0
Bank Sta=343.52,358.2
XS Rating Curve= 0 ,0
Exp/Cntr(USF)=0,0
Exp/Cntr=0.3,0.1

Type RM Length L Ch R = 1 ,5470    ,286.9,294.7,300.9
XS GIS Cut Line= 2
 1597115.4901095415687.9318271271597499.58655322416237.635070854
#Sta/Elev= 30
       0  789.16     5.6  786.46    34.9  777.74    69.8     760    78.8  756.77
    98.9  752.55   132.5  748.21   252.5   742.7   299.6  738.68   336.3  737.58
   342.3  736.51   354.2  731.89   361.8  731.15   371.4   731.9   381.4  736.33
   385.2  737.08   449.7  739.31   459.4  743.77   469.2  751.05   474.1   752.7
   498.5  752.98   515.1  759.19   546.7  761.32   561.9  764.41   576.5  771.71
   625.3  807.23   630.2   809.7   647.2  815.17   661.6  818.66   670.6  823.61
#Mann= 9 ,-1,0
       0      .1       0      90     .06       0     110      .1       0
     330     .05       0   354.2    .045       0   371.4     .05       0
     450     .06       0     460     .07       0     570      .1       0
Bank Sta=354.2,371.4
XS Rating Curve= 0 ,0
Exp/Cntr(USF)=0,0
Exp/Cntr=0.3,0.1

Type RM Length L Ch R = 1 ,5176    ,447.8,447,445.6
XS GIS Cut Line= 3
1597105.97119763415693.5868895821597039.01316759416132.872147317
1597132.78423641416213.762662225
#Sta/Elev= 30
       0  787.91    15.1  782.83    43.4  764.46    63.7  755.58   112.2  744.03
   148.2  742.91     177  737.89   209.3  735.88   294.3  732.75   326.7  733.42
     359  729.62   364.1  728.32   371.2  727.47   383.2  728.32   387.4  731.79
   391.4  736.93   393.9  739.07   403.6  744.68   411.7  745.31   427.8  744.69
     440   752.7   456.4  754.69   472.2  760.17   490.3  764.37   501.6  770.61
   509.2  776.42   518.6  781.34   530.3  790.39   554.1  804.51   568.2  811.69
#Mann= 7 ,-1,0
       0      .1       0      70     .06       0     170      .1       0
   364.1    .045       0   383.2     .06       0  484.36      .1       0
  504.36     .06       0
Bank Sta=364.1,383.2
XS Rating Curve= 0 ,0
Exp/Cntr(USF)=0,0
Exp/Cntr=0.3,0.1

Type RM Length L Ch R = 1 ,4729    ,353.1,350.5,348.6
XS GIS Cut Line= 3
1596637.29529088415667.6203418211596619.86610148416049.958301088
1596648.66435384416268.406006932
#Sta/Elev= 30
       0  824.61      53  802.94      93  780.93   133.1   770.8   161.1  765.38
   193.1     755   221.1  753.51   229.2  751.47   237.2  745.71   249.2  741.35
   253.2  737.62   261.2  726.43   265.2  723.47   277.2  721.35  286.11723.4415
   293.4  727.66   325.3  727.69   357.3  732.36   381.3  732.53   401.5  739.96
   441.8  744.92   453.9  749.69   490.2  760.27   518.5  772.26   522.5   775.9
   530.6  787.46   534.6  791.55   563.5  816.04     575  824.98   603.1     841
#Mann= 6 ,-1,0
       0      .1       0   265.2    .045       0  286.11      .1       0
     290     .05       0  392.74     .08       0  492.74      .1       0
Bank Sta=265.2,286.11
XS Rating Curve= 0 ,0
Exp/Cntr(USF)=0,0
Exp/Cntr=0.3,0.1

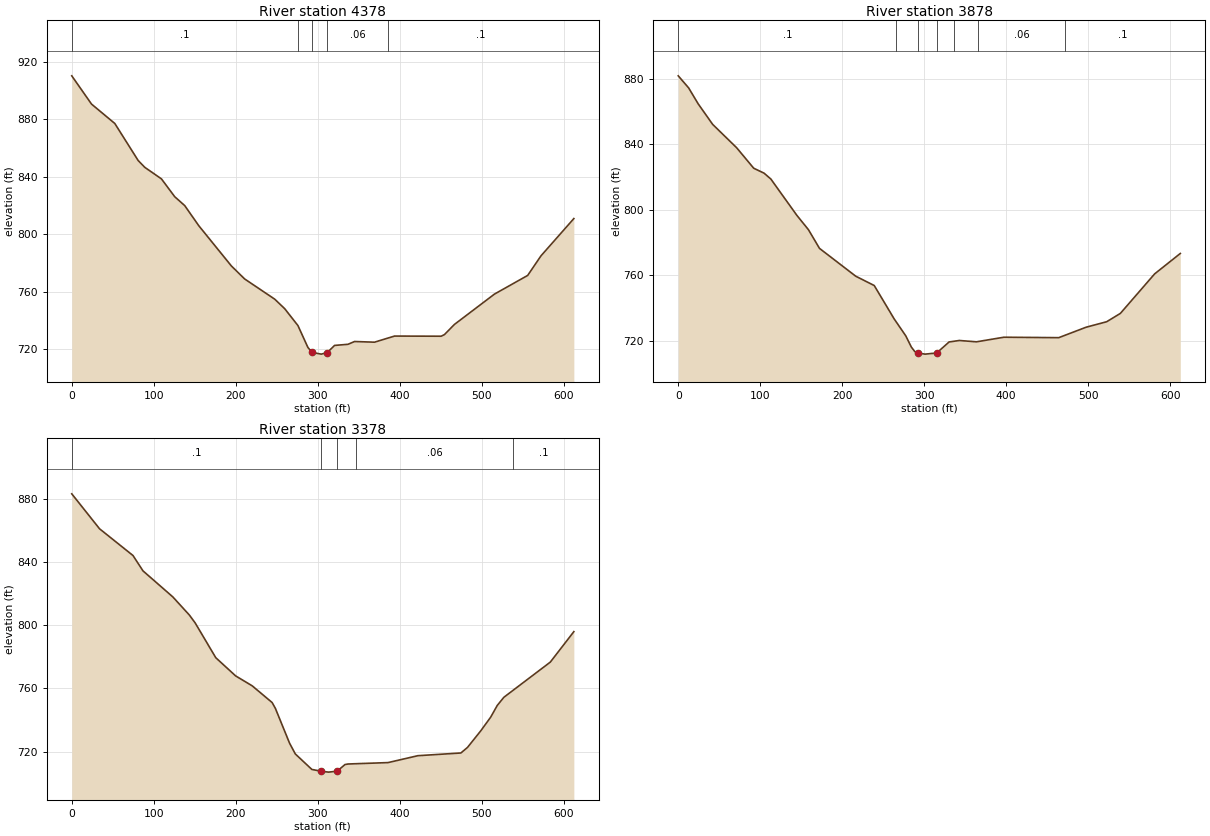
Type RM Length L Ch R = 1 ,4378    ,501.6,500,499
XS GIS Cut Line= 6
 1596225.1735595415692.8083480891596241.46584976415785.131982341
1596256.67218417415871.3004451691596269.70595075415945.159221336
1596287.08419684416043.6376989191596331.61724426416295.988244087
#Sta/Elev= 30
       0  910.19    24.1  890.54    52.5  877.07      81  851.33    89.1  846.58
   109.4  838.56   125.6  826.17   137.8  819.99     155  805.97   194.7  778.05
   210.9     769   247.6  754.95   259.7  748.38   275.9  736.62   288.1  721.37
  293.27717.8931   304.4  716.75   311.7  717.84   320.6   722.8   336.9  723.57
     345  725.52   369.3  725.05   393.7   729.3   450.6   729.2   454.6   730.3
   466.8  737.38   515.6  758.45   556.2  771.46   572.4  785.06   612.5  810.97
#Mann= 5 ,-1,0
       0      .1       0  276.25     .06       0  293.27    .045       0
   311.7     .06       0  386.25      .1       0
Bank Sta=293.27,311.7
XS Rating Curve= 0 ,0
Exp/Cntr(USF)=0,0
Exp/Cntr=0.3,0.1

Type RM Length L Ch R = 1 ,3878    ,498.5,500.1,501.6
XS GIS Cut Line= 6
1595702.09849018415808.3638912591595729.31497118415898.076310262
1595754.71682325415981.8077700881595776.49007368416053.577639669
  1595852.695958416304.772675335  1595879.912439416394.485094339
#Sta/Elev= 30
       0  881.93    12.7  874.55    24.2  864.91      42  852.26    71.2  838.02
    92.1  825.45   104.7  822.45     113  818.86   144.7  796.68   158.9  787.87
   172.3  776.49   216.6  759.45   239.1  753.78   263.5  733.32   277.6  723.01
   284.4  716.15   288.6  713.42  292.21712.5519   301.1  711.85   315.3  712.54
   330.4  719.28   342.9  720.19   363.8  719.37   397.3  722.18   464.2  721.91
   497.6   728.3   522.7  731.65   539.4  736.75   581.2   760.9   612.5  773.37
#Mann= 7 ,-1,0
       0      .1       0  266.25     .06       0  292.21    .045       0
   315.3     .06       0  336.25     .07       0  366.25     .06       0
  471.25      .1       0
Bank Sta=292.21,315.3
XS Rating Curve= 0 ,0
Exp/Cntr(USF)=0,0
Exp/Cntr=0.3,0.1

Type RM Length L Ch R = 1 ,3378    ,360.2,358.2,355.2
XS GIS Cut Line= 6
1595263.69647984415918.6228570941595289.32930259416098.050975919
 1595299.9352525416172.2972185021595314.07728459416271.292099252
1595324.68356259416345.5386699291595350.31638534416524.966788754
#Sta/Elev= 30
       0  883.09    33.9  860.97    74.7  844.05    86.9  834.33   123.2  817.91
   143.4  806.44   150.6  801.36   175.7  779.39   199.9  767.89   220.1  761.61
   244.4  751.05   248.4  747.34   265.7  725.32   272.7  718.51   292.9   708.7
  303.86707.6113   313.2     707   323.8   707.6   333.3   711.8   337.3  712.15
   385.8  713.03   422.2   717.4   474.7  719.11   482.8  722.66   498.9   733.1
   511.1  741.82   519.1  749.22   527.2  754.38   583.8  776.62   612.5  795.89
#Mann= 5 ,-1,0
       0      .1       0  303.86    .045       0   323.8      .1       0
  346.25     .06       0  538.75      .1       0
Bank Sta=303.86,323.8
XS Rating Curve= 0 ,0
Exp/Cntr(USF)=0,0
Exp/Cntr=0.3,0.1