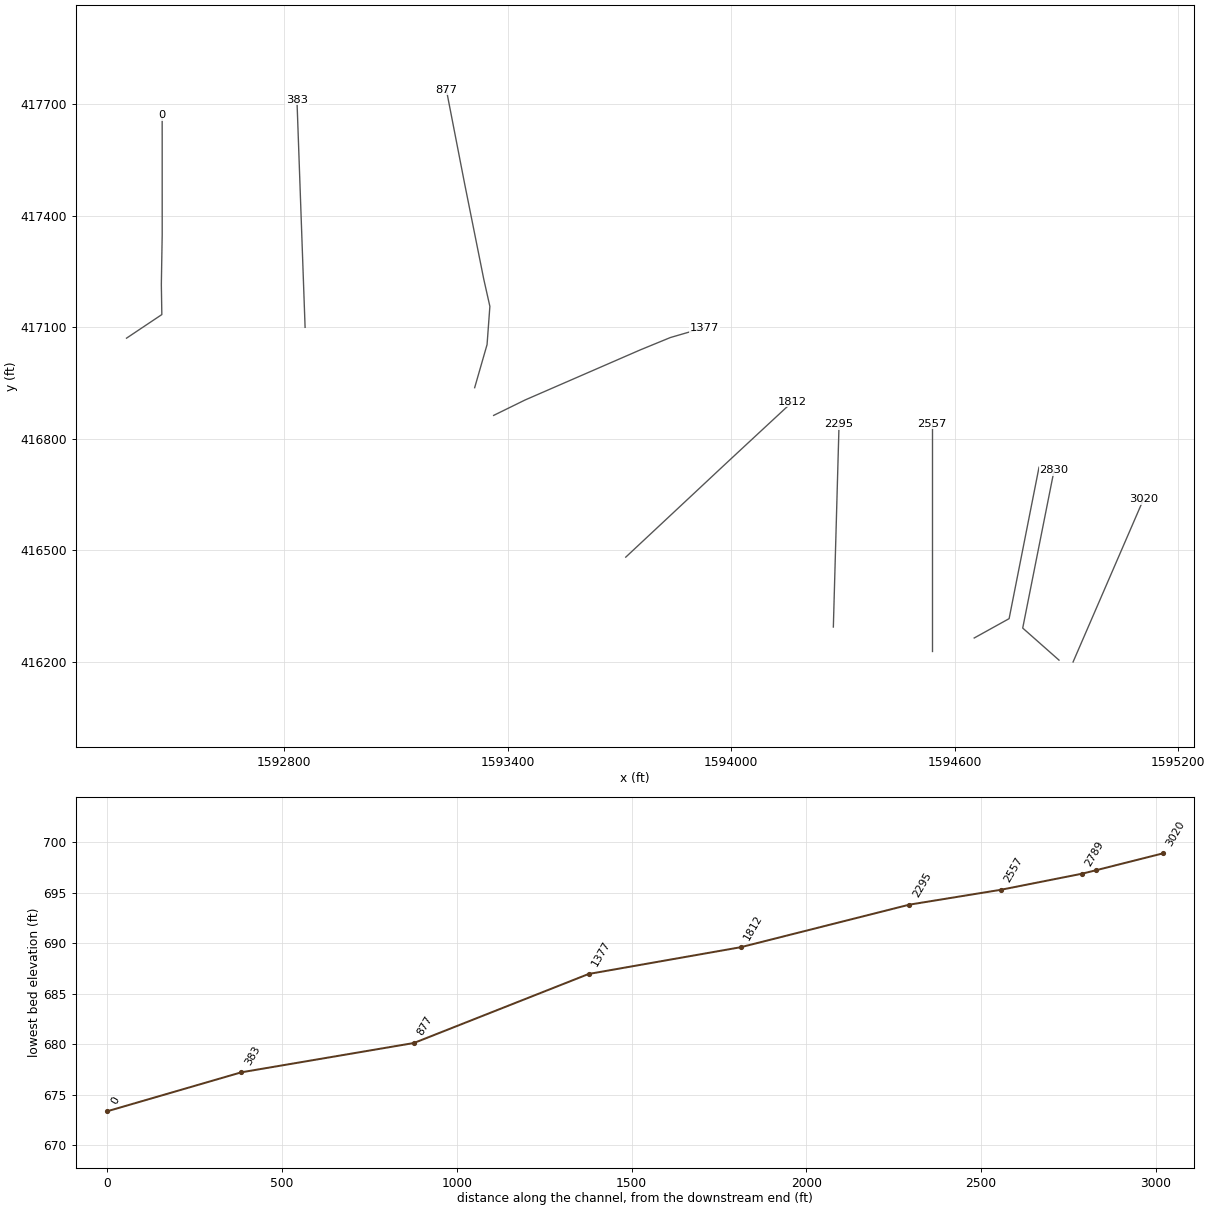
HEC-RAS study DOOLINRN.prj: DOOLINRN

--- DOOLINRN.g01 (geometry) --- (continued)

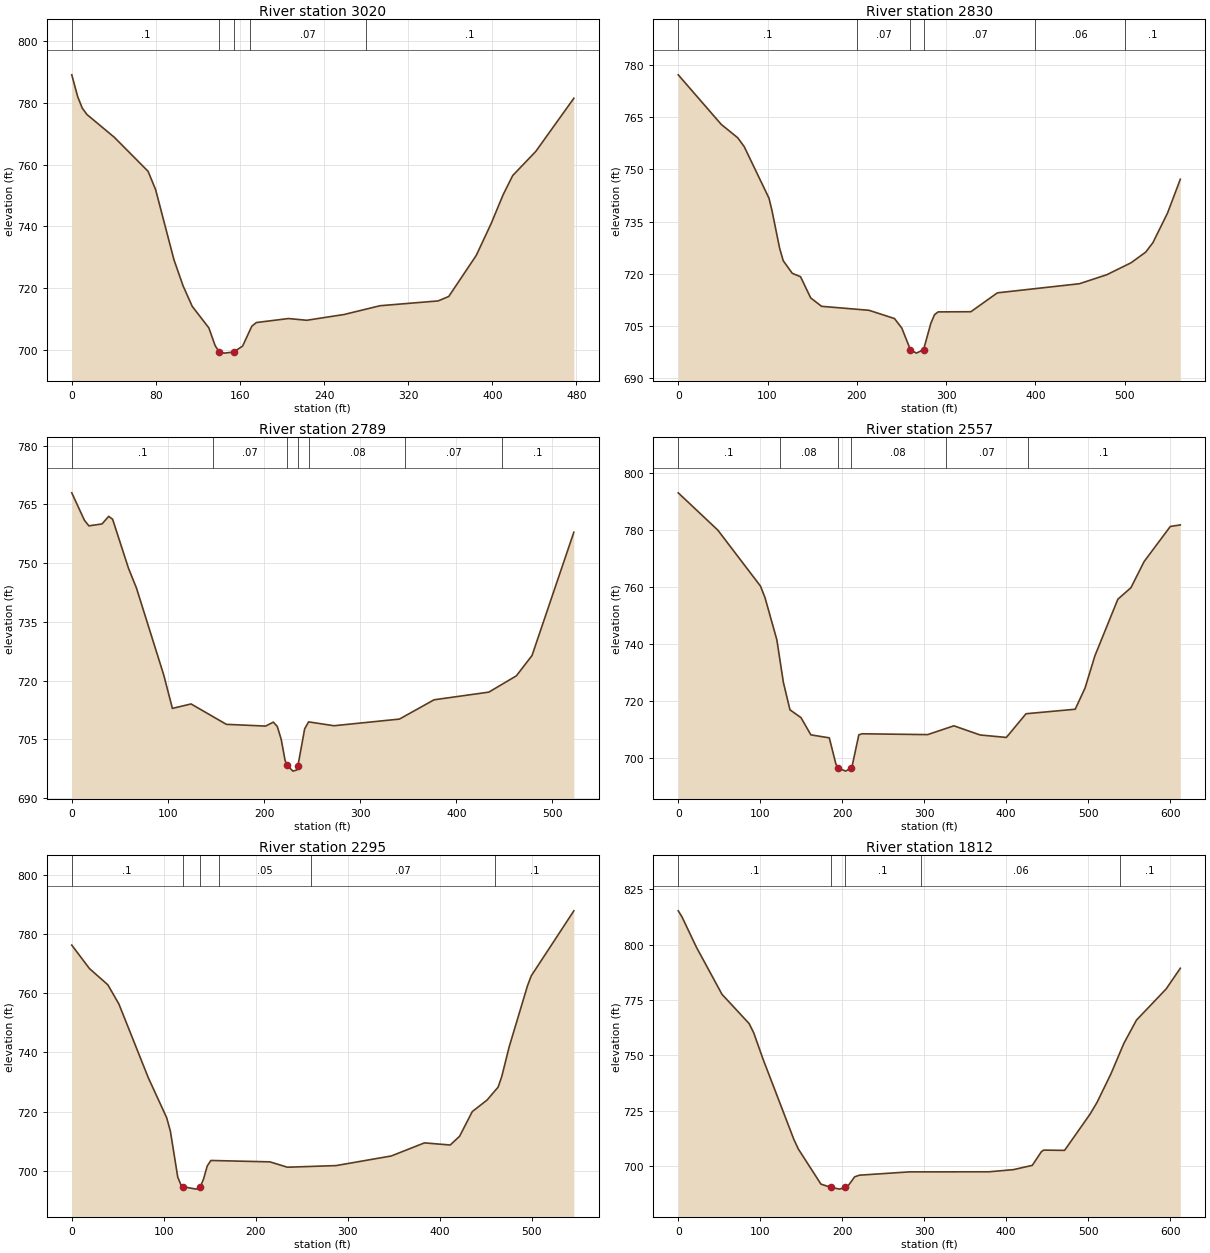
Type RM Length L Ch R = 1 ,3020    ,188.7,190.4,191.9
XS GIS Cut Line= 2
1594917.95598141416199.3187941051595107.33222801416637.814984146
#Sta/Elev= 30
       0  789.16     5.7     782      10  778.36    14.4   776.3    40.5  768.89
    72.6  757.86    79.8  751.87    97.2  729.18   105.9  720.68   114.6  714.04
   130.4  707.07   136.4  701.29  140.29699.2704   145.1  698.87  154.01699.2327
   162.5  701.15   171.3  707.63   175.6  708.79   206.1  710.09   223.5  709.53
     259   711.4   293.3  714.25   348.5  715.81   358.6  717.25   384.8  730.59
   398.9  740.88   410.3  750.23   419.4  756.46   441.4  764.32   477.6  781.55
#Mann= 5 ,-1,0
       0      .1       0  140.29    .045       0  154.01      .1       0
     170     .07       0     280      .1       0
Bank Sta=140.29,154.01
XS Rating Curve= 0 ,0
Exp/Cntr(USF)=0,0
Exp/Cntr=0.3,0.1

Type RM Length L Ch R = 1 ,2830    ,41.2,41,40.9
XS GIS Cut Line= 3
1594880.17053671416204.3225969531594782.77703846416290.556423529
1594866.91597939416714.645663834
#Sta/Elev= 30
       0  777.13    48.2  762.89    66.7  759.04    73.9  756.51   101.6  741.74
     105  738.17   113.5  727.42   117.6  723.76   127.7  720.14     137  719.15
   148.4  713.06   160.6  710.65   213.7  709.51   242.2  707.14   250.4  704.43
  260.01698.2285   266.7  697.21   274.8   698.2     283  705.81   287.1  708.25
   291.1  709.05   327.8   709.1   357.5  714.52   449.4  717.14     480  719.72
   507.2  723.15   523.6  726.21   531.7  728.93   548.1  737.44   562.4  747.14
#Mann= 6 ,-1,0
       0      .1       0  200.08     .07       0  260.01    .045       0
   274.8     .07       0  400.08     .06       0  500.08      .1       0
Bank Sta=260.01,274.8
XS Rating Curve= 0 ,0
Exp/Cntr(USF)=0,0
Exp/Cntr=0.3,0.1

Type RM Length L Ch R = 1 ,2789    ,231,232.1,233
XS GIS Cut Line= 3
 1594652.5868307416263.8705688591594746.25447661416315.919313698
1594826.54083881416723.236119276
#Sta/Elev= 30
       0  767.98    13.2  760.96    17.8  759.54    31.5  760.03    38.4  761.97
    42.5  761.23      59  748.71    67.3  743.65    95.6  721.49   104.7  712.89
   124.1  714.03   160.8  708.82   201.6  708.37   209.7  709.38   213.8  708.28
   217.9  704.95   221.9  699.61  224.06698.3164   230.1  696.86   234.2  697.16
   235.3  698.28   242.3  707.69   246.4  709.45   272.7  708.46   340.9  710.16
   376.9  715.09   433.9  717.05   462.5  721.21   478.8  726.41   522.3  757.91
#Mann= 7 ,-1,0
       0      .1       0  147.16     .07       0  224.06    .045       0
   235.3     .07       0  247.16     .08       0  347.16     .07       0
  447.16      .1       0
Bank Sta=224.06,235.3
XS Rating Curve= 0 ,0
Exp/Cntr(USF)=0,0
Exp/Cntr=0.3,0.1

Type RM Length L Ch R = 1 ,2557    ,261.6,261.5,260.9
XS GIS Cut Line= 2
1594538.68717512416228.2132455961594538.68717512416840.713332932
#Sta/Elev= 30
       0  792.98    48.3  779.89   100.3  760.25   105.8  756.25   120.3  741.39
   128.3  726.39   136.3   716.8   149.8  714.04   161.8  708.01   184.3  706.95
   192.3  697.81   194.9  696.38   204.3  695.27  210.41696.3317   212.3  697.26
   220.3     708   224.3  708.38   304.3  708.09   336.3  711.18   368.3  707.96
   400.3   707.1   424.3  715.42   484.3     717   496.3  724.46   508.3  735.75
   536.3  755.62   552.3  759.68   568.3  768.83   600.3  781.17   612.5  781.71
#Mann= 6 ,-1,0
       0      .1       0  123.75     .08       0   194.9    .045       0
  210.41     .08       0  326.25     .07       0  426.25      .1       0
Bank Sta=194.9,210.41
XS Rating Curve= 0 ,0
Exp/Cntr(USF)=0,0
Exp/Cntr=0.3,0.1

Type RM Length L Ch R = 1 ,2295    ,489.2,482.5,474.4
XS GIS Cut Line= 2
1594274.41317957416293.3586816371594289.72137117 416838.88696402
#Sta/Elev= 30
       0  776.22    19.2  768.31    39.2  762.82    51.2  756.35    83.2  731.42
   103.2  717.88   107.2  713.35   115.2  697.85   119.2  694.81  120.52694.6549
   135.2   693.8  139.74 694.669   143.2  697.18   147.2   701.6   151.2  703.48
   215.3  703.01   234.4   701.2   287.3  701.75   347.3     705   383.3  709.42
   411.3   708.7   421.5  711.65   435.3  719.99   451.4  723.89   463.4  728.26
   467.4  731.89   475.4  741.84   495.4  762.56   499.4  765.84   545.7   787.8
#Mann= 6 ,-1,0
       0      .1       0  120.52    .045       0  139.74      .1       0
     160     .05       0     260     .07       0     460      .1       0
Bank Sta=120.52,139.74
XS Rating Curve= 0 ,0
Exp/Cntr(USF)=0,0
Exp/Cntr=0.3,0.1

Type RM Length L Ch R = 1 ,1812    ,439.4,435.4,432.3
XS GIS Cut Line= 6
 1593717.1095292416481.4213220431593904.04485087416656.505617539
1593976.99844511416724.9093521191594031.89859778416776.075260292
1594096.02773463416835.689642365 1594164.7720197416899.528097371
#Sta/Elev= 30
       0  815.34     4.6   812.6    22.1  798.96    53.4  777.61    86.5  764.39
    92.1  760.21   103.4   748.4   141.1  712.02   146.6  707.67   174.1  691.85
     186  690.42   196.8  689.59  204.04 690.492   208.1  691.52   215.2  695.14
   221.1  695.89   281.7  697.38   379.1  697.42     409   698.4   431.9  700.33
     443   706.5   445.8  707.22   471.3   707.1   502.4  723.48   510.9  728.78
   527.9   741.7   543.5  755.34     559  765.96   595.3  780.08   612.5  789.39
#Mann= 5 ,-1,0
       0      .1       0     186    .045       0  204.04      .1       0
  296.12     .06       0  538.73      .1       0
Bank Sta=186,204.04
XS Rating Curve= 0 ,0
Exp/Cntr(USF)=0,0
Exp/Cntr=0.3,0.1

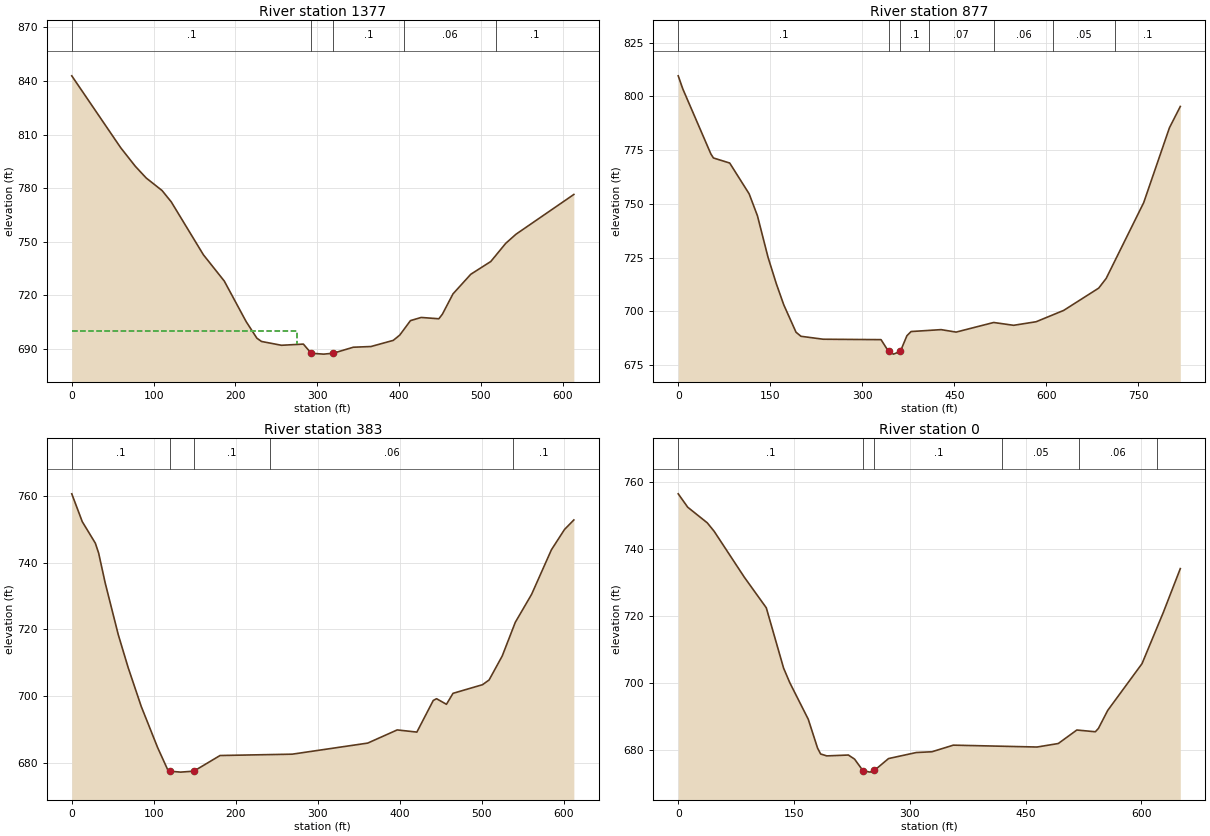
Type RM Length L Ch R = 1 ,1377    ,488.1,500,516.8
XS GIS Cut Line= 6
 1593362.4391275416862.812241673 1593446.6597596416904.217998758
1593526.87088525416939.1818395851593756.04431142 417039.07927759
1593836.98706293417072.3636598441593928.04495168417098.899367929
#Sta/Elev= 30
       0  842.89    59.8  802.61    77.6  792.24      91  785.63   110.4   778.6
   121.6  772.26   160.9  742.61   186.4   727.9   213.2  705.13   226.3  695.86
   231.9  694.04   256.3   691.9   283.1  692.56   292.7  687.41   307.9  686.94
  319.48687.4342   344.2  690.81   365.7   691.2     393  694.65   400.9  697.61
     414  705.72   427.1  707.49   448.7  706.75     453  709.31     466  720.71
   487.7  731.68   512.2  738.85   530.5  749.05     543  754.13   613.7  776.41
#Mann= 5 ,-1,0
       0      .1       0   292.7    .045       0  319.48      .1       0
  406.35     .06       0  518.87      .1       0
#XS Ineff= 2 , 0
          274.77   699.7
Permanent Ineff=
       F       F
Bank Sta=292.7,319.48
XS Rating Curve= 0 ,0
Exp/Cntr(USF)=0,0
Exp/Cntr=0.3,0.1

Type RM Length L Ch R = 1 ,877     ,494.4,493.8,490.9
XS GIS Cut Line= 6
1593311.50320576416937.4006751781593344.78824417417053.394865751
1593352.33514509417156.1564712521593335.90440367417229.448647499
1593284.42189509417486.8506917511593235.49160735 417739.13513809
#Sta/Elev= 30
       0   809.6     7.4  803.54    53.2  773.25    57.4  771.38    83.9  769.02
   115.6  754.68   129.1  744.48   146.4  725.13   159.9  712.84     172  703.05
     192   690.3     200  688.41   236.4  687.04   330.5  686.85   342.8  681.37
   350.9  680.11  362.04681.3863   372.7  688.66   379.5  690.62   428.4  691.51
   452.9  690.36   514.1  694.83   546.7  693.52   583.3  695.18   628.2  700.45
   685.3  710.82   697.5  715.35   758.6  750.58   800.6  785.44   818.3  795.35
#Mann= 7 ,-1,0
       0      .1       0   342.8    .045       0  362.04      .1       0
  408.83     .07       0  513.83     .06       0  611.33     .05       0
  711.33      .1       0
Bank Sta=342.8,362.04
XS Rating Curve= 0 ,0
Exp/Cntr(USF)=0,0
Exp/Cntr=0.3,0.1

Type RM Length L Ch R = 1 ,383     ,384.4,383.3,381.6
XS GIS Cut Line= 6
1592856.26100601417099.7762771081592852.91455601417193.466706527
1592849.79185884417280.910757361  1592847.115355417355.863035275
1592840.86930451417530.7514650211592834.40081351417711.886273352
#Sta/Elev= 30
       0  760.63    12.8  752.29    28.8  745.82    32.8  742.85    40.8  733.89
    56.8  718.35    68.8  708.54    84.8  696.87   104.8  684.54   116.8  678.06
  119.75677.4847   132.8  677.21   148.9   677.5   180.9  682.19   268.9  682.59
     361  685.91     397  689.86     421  689.21     441  698.69     445  699.22
   457.1  697.54   465.1  700.83   501.1  703.42   509.1  704.83   525.1  712.01
   541.1  722.13     561  730.52   585.1  743.84   601.1  749.94   612.5   752.8
#Mann= 5 ,-1,0
       0      .1       0  119.75    .045       0   148.9      .1       0
  241.25     .06       0  538.75      .1       0
Bank Sta=119.75,148.9
XS Rating Curve= 0 ,0
Exp/Cntr(USF)=0,0
Exp/Cntr=0.3,0.1

Type RM Length L Ch R = 1 ,0       ,,,
XS GIS Cut Line= 6
1592376.87637665417070.6444143211592471.68554299417134.149293685
1592470.37252968417214.1673050431592470.59942039417229.431298121
1592472.65506498 417348.665679551592472.59059964417670.572038115
#Sta/Elev= 30
       0  756.51    12.3  752.51    37.6  747.85    46.5  745.33    85.7  731.58
   114.1  722.46   136.5  704.46   144.5  700.11   168.5  689.15   180.5  680.57
   184.5  678.78   192.5  678.21   220.5  678.47   228.5  677.25   239.3  673.81
   248.5  673.36   254.1 673.856   272.5  677.41   308.5  679.22   328.7  679.44
   356.5  681.42     465  680.86   492.5  681.91   516.5  685.94   540.5  685.42
   544.5  686.42   556.5  691.79     601  705.78   628.5  721.03   650.6  734.17
#Mann= 6 ,-1,0
       0      .1       0   239.3    .045       0   254.1      .1       0
  419.89     .05       0  519.89     .06       0  619.89      .1       0
Bank Sta=239.3,254.1
XS Rating Curve= 0 ,0
Exp/Cntr(USF)=0,0
Exp/Cntr=0.3,0.1
LCMann Table=0

Chan Stop Cuts=-1
Use User Specified Reach Order=0
Composite Channel Slope=5